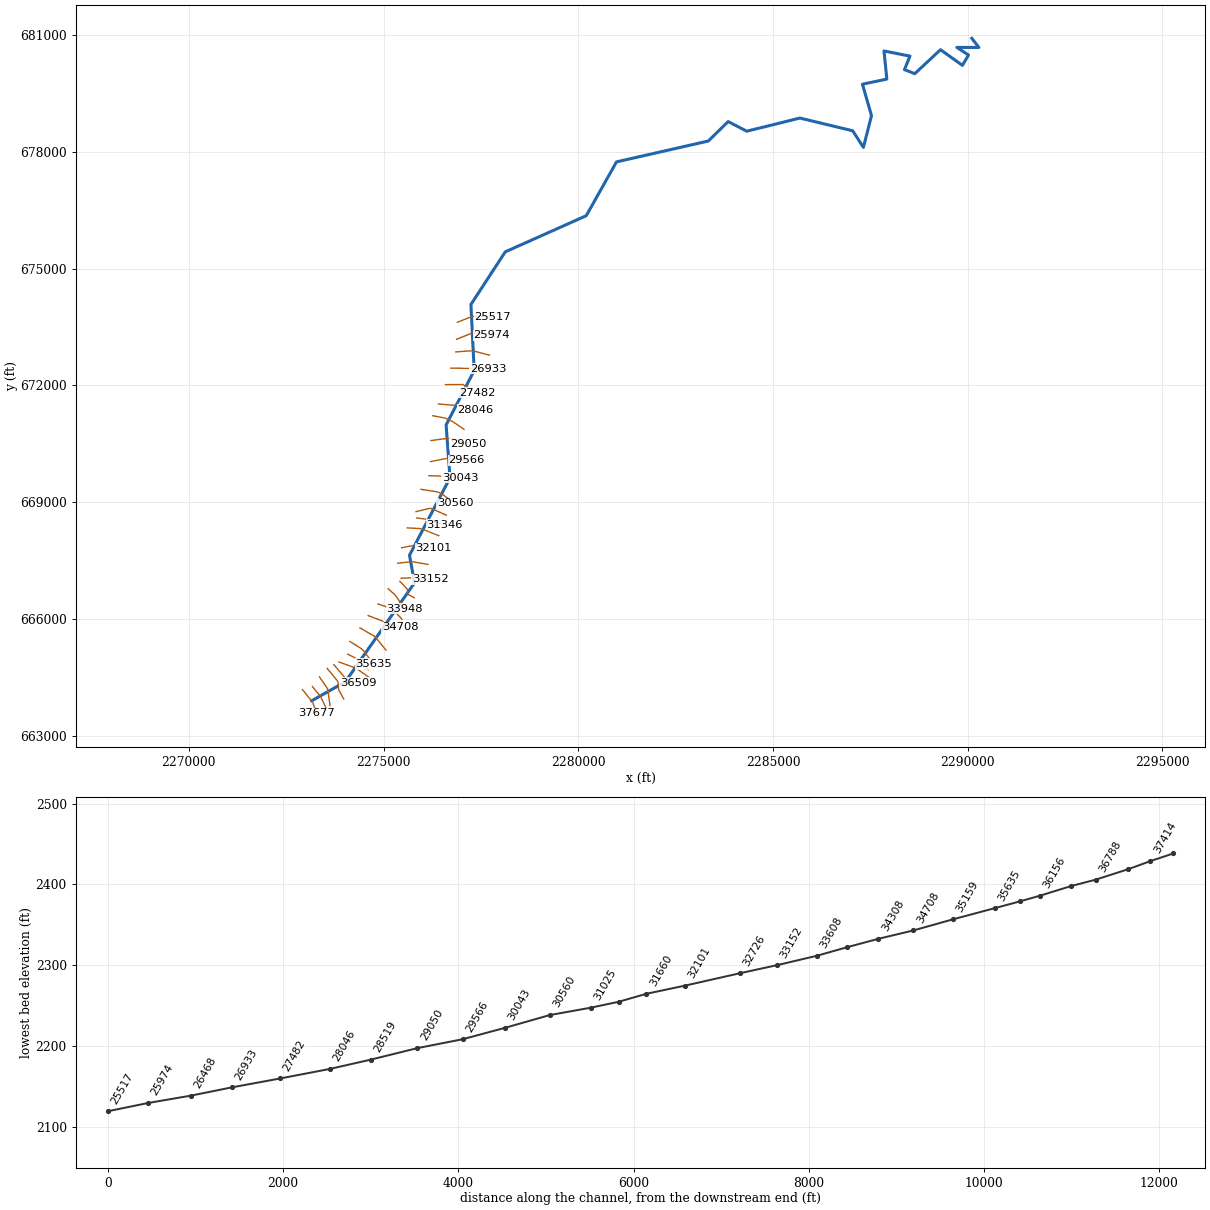
--- BEAVCK1.prj (project) ---

Proj Title=BEAVCK1
Current Plan=p01
Default Exp/Contr=0,0
English Units
Geom File=g01
Flow File=f01
Plan File=p01
BEGIN DESCRIPTION:
----------MODEL BY WOOD PLC 2022----------
AFH study
Randolph County, WV
HEC-RAS Version: RAS 6.2
Vertical Datum: NAVD88
Projection: NAD 1983 StatePlane West Virginia S FIPS 4702 (US Feet)
Terrain: 1-meter LIDAR (FEMA Region III 3DEP collected 2016-2018)
Land Use: 2019 NLCD
Hydrologic Method:
WV SIR2010-5033 regression equations
Additional Model Notes:
Right overbank from RS 7094 - 9395 has unbounded floodplain due to parallel flow with main stem
END DESCRIPTION:
DSS Export Rating Curves= 0
DSS Export Rating Curve Sorted= 0
DSS Export Volume Flow Curves= 0
DXF OffsetX= 0
DXF OffsetY= 0
DXF ScaleX= 0
DXF ScaleY= 0

--- BEAVCK1.p01 (plan) ---

Plan Title=Floodplain
Program Version=6.20
Short Identifier=Floodplain
Geom File=g01
Flow File=f01
Subcritical Flow
K Sum by GR= 0
Std Step Tol= 0.01
Critical Tol= 0.01
Num of Std Step Trials= 20
Max Error Tol= 0.3
Flow Tol Ratio= 0.001
Split Flow NTrial= 30
Split Flow Tol= 0.02
Split Flow Ratio= 0.02
Log Output Level= 0
Friction Slope Method= 1
Unsteady Friction Slope Method= 2
Unsteady Bridges Friction Slope Method= 1
Parabolic Critical Depth
Global Vel Dist= 0 , 0 , 0
Global Log Level= 0
CheckData=True
Encroach Param=-1 ,0,0, 0
Mapping Interval=1HOUR
Computation Time Step Use Courant=        0
Computation Time Step Use Time Series=    0
Computation Time Step Count To Double=0
Computation Time Step Max Doubling=0
Computation Time Step Max Halving=0
Computation Time Step Residence Courant=0
Run HTab= 0
Run UNet= 0
Run Sediment= 0
Run PostProcess= 0
Run WQNet= 0
Run RASMapper=-1
UNET Theta= 0
UNET Theta Warmup= 0
UNET ZTol= 0
UNET ZSATol= 0
UNET MxIter= 0
UNET Max Iter WO Improvement= 0
UNET MaxInSteps= 0
UNET DtIC= 0
UNET DtMin= 0
UNET MaxCRTS= 0
UNET WFStab= 0
UNET SFStab= 0
UNET WFX= 1
UNET SFX= 1
UNET Gravity=32.174
UNET 1D Methodology=Finite Difference
UNET DSS MLevel= 1
UNET Pardiso=0
UNET DZMax Abort= 0
UNET Use Existing IB Tables= 0
UNET Froude Reduction=False
UNET Froude Limit= 0
UNET Froude Power= 0
UNET D1 Cores= 0
UNET WindReference=Eulerian
UNET WindDragFormulation=Hsu (1988)
UNET D2 Coriolis=0
UNET D2 Cores= 0
UNET D2 Theta= 1
UNET D2 Theta Warmup= 1
UNET D2 Z Tol= 0.01
UNET D2 Volume Tol= 0.01
UNET D2 Max Iterations= 20
UNET D2 Equation= 0
UNET D2 RampUpFraction=0.1
UNET D2 TimeSlices= 1
UNET D2 Turbulence Formulation=Non-Conservative (original)
UNET D2 Eddy Viscosity=0.3
UNET D2 Transverse Eddy Viscosity=0.1
UNET D2 Smagorinsky Mixing=0
UNET D2 BCVolumeCheck=0
UNET D2 Cores=0
UNET D2 SolverType=PARDISO (Direct)
UNET D2 Minimum Iterations= 2147483647
UNET D2 Maximum Iterations= 2147483647
UNET D2 Restart Number= 10
UNET D2 Relaxation Coeff=1.3
UNET D2 SOR Precondition Iterations= 10
UNET D2 ILUT Maximum Fill= 8
UNET D2 ILUT Tolerance=1E-08
UNET D1D2 MaxIter= 0
UNET D1D2 ZTol=0.01
UNET D1D2 QTol=0.1
UNET D1D2 MinQTol=1
Write IC File= 0
Write IC File at Fixed DateTime=0
Write IC File at Sim End=0
Echo Input=False
Echo Parameters=False
Echo Output=False
Write Detailed= 0
HDF Write Warmup=0
HDF Write Time Slices=0
HDF Flush=0
HDF Compression= 1
HDF Chunk Size= 1
HDF Spatial Parts= 1
HDF Use Max Rows=0
HDF Fixed Rows= 1
Calibration Method= 0
Calibration Iterations= 20
Calibration Max Change=0.05
Calibration Tolerance=0.2
Calibration Maximum=1.5
Calibration Minimum=0.5
Calibration Optimization Method= 1
WQ AD Non Conservative
WQ ULTIMATE=-1
WQ Max Comp Step=1HOUR
WQ Output Interval=15MIN
WQ Output Selected Increments= 0
WQ Output face flow=0
WQ Output face velocity=0
WQ Output face area=0
WQ Output face dispersion=0
WQ Output cell volume=0
WQ Output cell surface area=0
WQ Output cell continuity=0
WQ Output cumulative cell continuity=0
WQ Output face conc=0
WQ Output face dconc_dx=0
WQ Output face courant=0
WQ Output face peclet=0
WQ Output face adv mass=0
WQ Output face disp mass=0
WQ Output cell mass=0
WQ Output cell source sink temp=0
WQ Output nsm pathways=0
WQ Output nsm derived pathways=0
WQ Create Restart=0
WQ Fixed Restart=0
WQ System Summary=0
WQ Write To DSS=0
Sorting and Armoring Iterations= 10
XS Update Threshold= 0.02
Bed Roughness Predictor= 0
Hydraulics Update Threshold= 0.02
Energy Slope Method= 1
Volume Change Method= 1
Sediment Retention Method= 0
Sediment TS Multiplier= 1
Warm Up Method= 0
XS Weighting Method= 0
Number of US Weighted Cross Sections= 1
Number of DS Weighted Cross Sections= 1
Upstream XS Weight=0
Main XS Weight=1
Downstream XS Weight=0
Number of DS XS's Weighted with US Boundary= 1
Upstream Boundary Weight= 1
Weight of XSs Associated with US Boundary= 0
Number of US XS's Weighted with DS Boundary= 1
Downstream Boundary Weight= 0.5
Weight of XSs Associated with DS Boundary= 0.5
Percentile Method= 0
Sediment Output Level= 3
Mass or Volume Output= 0
Output Increment Type= 1
Profile and TS Output Increment= 1
Transport Output Increment 1
XS Output Flag= 0
XS Output Increment= 10
Read HDF5 Sediment Hotstart= 0
Sediment Hotstart Type= 0
Write Gradation File= 0
Read Gradation Hotstart= 0
Write HDF5 File= 1
Write Binary Output= 1
Write DSS Sediment File= 0
DSS Sediment Output Type= 1
SV Curve= 0
Specific Gage Flag= 0
Subcell Erosion Methods= 0
Subcell Deposition Methods= 0
Advection Scheme= 1
Matrix Solver= 0
Implicit Weighting Factor= 1
Maximum Outer Loop Convergence Iterations= 5
Convergence Maximum Absolute= 0.001
Convergence RMSE= 0.0001
Grain Fractions Max Abs Error= 0.001
Max Subgrid Regions= 1
Max Subgrid Length Scale= 3.402823E+38
Initial Layer Thickness= 3.402823E+38
Min Layer Thickness= 3.402823E+38
Max Layer Thickness= 3.402823E+38
Number of Layers= 5

--- BEAVCK1.f01 (steady flow) ---

Flow Title=Flow
Program Version=6.20
Number of Profiles= 1
Profile Names=P100yr
River Rch & RM=BEAVCK1,Main,37677
     367
River Rch & RM=BEAVCK1,Main,33608
     429
River Rch & RM=BEAVCK1,Main,33152
     481
River Rch & RM=BEAVCK1,Main,29566
     620
River Rch & RM=BEAVCK1,Main,26468
     788
River Rch & RM=BEAVCK1,Main,25517
     879
River Rch & RM=BEAVCK1,Main,21583
    1040
River Rch & RM=BEAVCK1,Main,19514
    1160
River Rch & RM=BEAVCK1,Main,15716
    1500
River Rch & RM=BEAVCK1,Main,10296
    1680
Boundary for River Rch & Prof#=BEAVCK1,Main            , 1
Up Type= 0
Dn Type= 3
Dn Slope=0.00123
DSS Import GetInterval= 0
DSS Import GetPeak= 0
DSS Import FillOption= 0

--- BEAVCK1.g01 (geometry) ---

Geom Title=Geometry
Program Version=6.20

River Reach=BEAVCK1         ,Main
Reach XY= 30
     2273153.002      663899.897     2274017.585      664387.397
     2275793.345      666926.611     2275665.306      667638.417
     2276705.263      669624.602     2276605.074      670983.788
      2277326.45      672380.363     2277242.005       674075.98
     2278124.882      675428.236 2280203.9093955676355.477438189
     2280980.477      677737.374     2283337.822      678273.335
      2283848.05      678772.854     2284324.622      678525.189
2285689.71730787678863.1315483042287044.95828658678536.985978225
     2287321.217      678109.563     2287528.201      678928.179
     2287295.158      679731.351     2287921.739       679864.42
     2287849.273      680586.166     2288515.105      680453.632
     2288374.415      680107.326     2288639.789      680002.657
     2289299.169      680617.673     2289862.431        680216.7
     2290020.451      680482.317     2289718.894      680677.485
     2290286.355      680675.457     2290103.661       680910.14

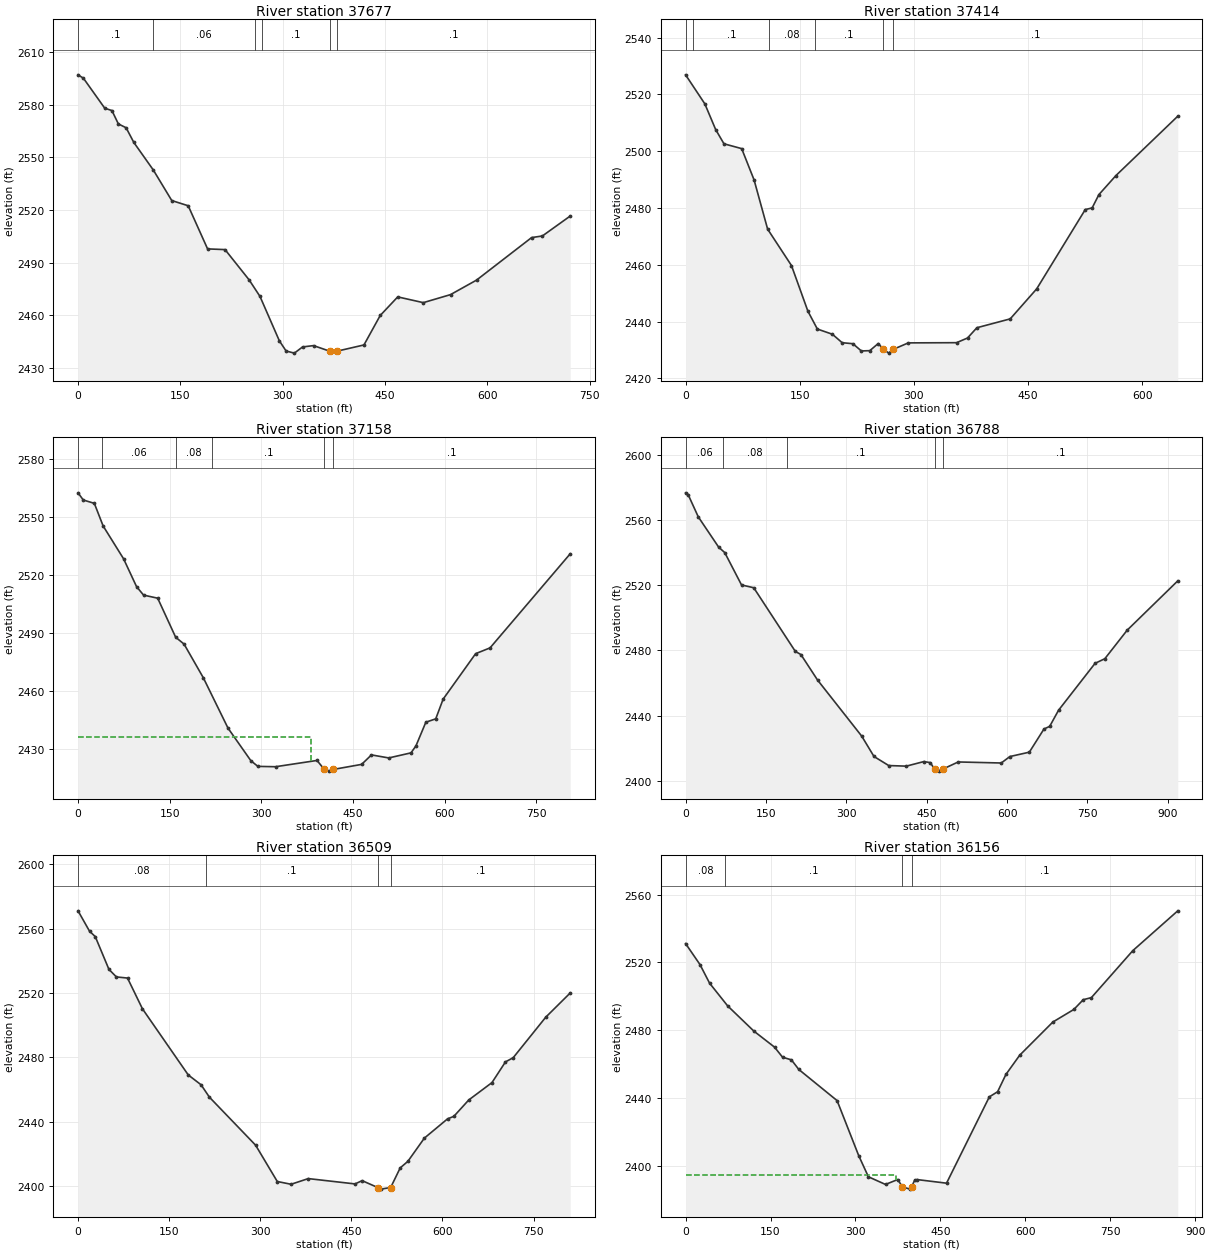
Type RM Length L Ch R = 1 ,37677   ,262.1,262.8,262.5
XS GIS Cut Line= 4
 2272915.6182147664187.7479505252273106.57524275663952.976835282
2273176.68941588663874.3122443572273275.44913256663576.892768494
#Sta/Elev= 30
       0 2597.09     7.9 2595.16    39.2 2578.04    49.7 2576.71    59.1  2569.1
    70.5  2566.9    81.8 2558.52   110.3 2542.84   137.4 2525.39   161.5 2522.42
   189.9 2497.82   215.5 2497.42   250.8 2480.15   266.7 2470.72   295.1 2445.39
     305 2439.59   317.1 2438.38   329.1 2441.91   345.2 2442.67   368.8  2439.5
  379.952439.529   419.1 2443.04   442.9 2459.84   468.6 2470.45   506.1 2467.17
     546 2471.75   584.1 2480.02   664.8 2504.27   680.6 2505.19   721.4 2516.56
#Mann= 6 ,-1,0
       0      .1       0     110     .06       0     260     .08       0
     270      .1       0   368.8    .045       0  379.95      .1       0
Bank Sta=368.8,379.95
XS Rating Curve= 0 ,0
Exp/Cntr=0.3,0.1

Type RM Length L Ch R = 1 ,37414   ,260.1,255.5,251.8
XS GIS Cut Line= 4
2273172.17279557664268.6705553512273303.59295175664103.335520164
2273365.06366996664039.7451220152273517.68062551663728.152171085
#Sta/Elev= 30
       0 2526.93    25.3  2516.7    39.5 2507.66    50.4 2502.63    73.7 2500.93
      90 2489.89   107.8 2472.55   139.1 2459.74   160.7 2443.64   173.1 2437.36
   192.9 2435.52   205.7 2432.54   219.8 2432.19   230.9 2429.64     242 2429.74
   253.1 2432.26   259.32430.406   266.9 2428.87   272.4 2430.15   292.6 2432.48
     356 2432.55   370.4  2434.2   382.7 2437.82   426.5 2440.94   461.3 2451.53
   525.1 2479.46   534.1 2480.03     543 2484.73   565.3 2491.42   646.6 2512.35
#Mann= 6 ,-1,0
       0     .06       0      10      .1       0     110     .08       0
     170      .1       0   259.3    .045       0   272.4      .1       0
Bank Sta=259.3,272.4
XS Rating Curve= 0 ,0
Exp/Cntr(USF)=0,0
Exp/Cntr=0.3,0.1

Type RM Length L Ch R = 1 ,37158   ,370.4,370.7,370
XS GIS Cut Line= 4
2273354.13872719664512.306628239 2273560.9054394664209.109408939
2273577.44631149664106.7721017932273625.97875216663775.334570128
#Sta/Elev= 30
       0 2562.74     8.6 2559.03    26.7  2557.3    41.1  2545.6    74.6  2528.6
    95.8 2514.22   107.3 2509.84   130.4 2508.25   159.8 2488.06   173.6  2484.5
   205.2 2467.03   245.5 2441.05   282.9  2424.2   294.4 2421.26   323.3 2421.09
   391.2 2424.33  403.09  2419.7   411.5 2418.81   418.1  2419.7   464.2  2422.3
   480.3  2427.2   508.6 2425.63     545 2428.26   553.1 2431.85   569.3 2444.11
   585.5 2445.85   597.6 2456.04   650.8 2479.56   674.4 2482.55   805.6 2531.21
#Mann= 6 ,-1,0
       0      .1       0      40     .06       0     160     .08       0
     220      .1       0  403.09    .045       0   418.1      .1       0
#XS Ineff= 2 , 0
           380.8 2436.64
Permanent Ineff=
       F       F
Bank Sta=403.09,418.1
XS Rating Curve= 0 ,0
Exp/Cntr=0.3,0.1

Type RM Length L Ch R = 1 ,36788   ,267.1,279,286.3
XS GIS Cut Line= 4
 2273551.5703269 664731.473308192273825.90272091664397.439019211
 2273843.9022533664190.6345668912273976.25100347663945.362415695
#Sta/Elev= 30
       0 2576.73     4.9 2575.53    23.7 2561.97    61.7  2543.4    73.1 2540.04
   104.4 2520.18   127.2 2518.47   204.8 2479.39   215.2 2477.47   246.2 2461.85
   328.7 2427.38   351.6 2414.89   379.1 2409.32   411.9 2408.96   444.6 2411.76
   456.6 2411.13   464.6 2407.21   472.7  2405.9   480.7 2407.24   508.8 2411.53
   589.1 2410.89   605.2 2414.85   641.5 2417.54   668.8 2431.75   679.5 2433.38
     696 2443.27   764.2 2472.08   782.4  2474.9   824.1 2492.42   918.5 2522.69
#Mann= 5 ,-1,0
       0     .06       0      70     .08       0     190      .1       0
   464.6    .045       0   480.7      .1       0
Bank Sta=464.6,480.7
XS Rating Curve= 0 ,0
Exp/Cntr=0.3,0.1

Type RM Length L Ch R = 1 ,36509   ,351.6,352.8,353.4
XS GIS Cut Line= 4
2273718.94712094664830.6719242592274022.27332011664478.699070505
2274080.45853441664447.2218234212274346.58435067 664361.37478592
#Sta/Elev= 30
       0 2571.13    18.9 2558.49    28.4 2555.09    50.9 2534.72    63.2 2530.02
    81.5 2529.32     106 2510.24   181.5 2469.07   202.6 2462.96   216.3 2455.27
   292.4 2425.39   328.1 2402.81   350.8 2401.09   379.1 2404.62   456.1 2401.31
   467.8 2403.34   494.1 2398.97   498.6 2398.07  514.782399.067   530.5 2411.28
   543.1 2415.35   570.3  2429.8   608.5 2441.79   618.8 2443.32   643.4 2453.53
   681.6 2464.32   703.8  2477.2   716.5 2479.78   770.1 2504.97   810.4 2520.05
#Mann= 4 ,-1,0
       0     .08       0     210      .1       0   494.1    .045       0
  514.78      .1       0
Bank Sta=494.1,514.78
XS Rating Curve= 0 ,0
Exp/Cntr(USF)=0,0
Exp/Cntr=0.3,0.1

Type RM Length L Ch R = 1 ,36156   ,235.1,232.4,230.6
XS GIS Cut Line= 4
2273852.28821192664896.2981134422274148.95150961 664789.92003628
2274300.84688991 664728.921853422274621.33811344664505.833594067
#Sta/Elev= 30
       0 2531.15    25.4 2518.77    42.4 2507.77    74.3 2494.37   120.5 2479.52
   157.1 2470.03   171.3 2464.07   186.9 2462.52     200 2456.84   267.6 2438.47
   305.8 2405.97   322.9 2393.51   353.1 2388.99   374.7  2391.9  382.942387.576
   396.2 2386.23  399.032387.573   404.8 2391.57   409.2 2391.85   460.9 2389.74
   536.5 2440.68   551.1 2443.71   565.8 2453.92   590.1 2465.25   648.6 2484.82
   685.7 2492.26   702.4 2498.03   716.7 2499.24   789.9 2526.97   869.3 2550.47
#Mann= 4 ,-1,0
       0     .08       0      70      .1       0  382.94    .045       0
  399.03      .1       0
#XS Ineff= 2 , 0
           372.4 2394.37
Permanent Ineff=
       F       F
Bank Sta=382.94,399.03
XS Rating Curve= 0 ,0
Exp/Cntr=0.3,0.1

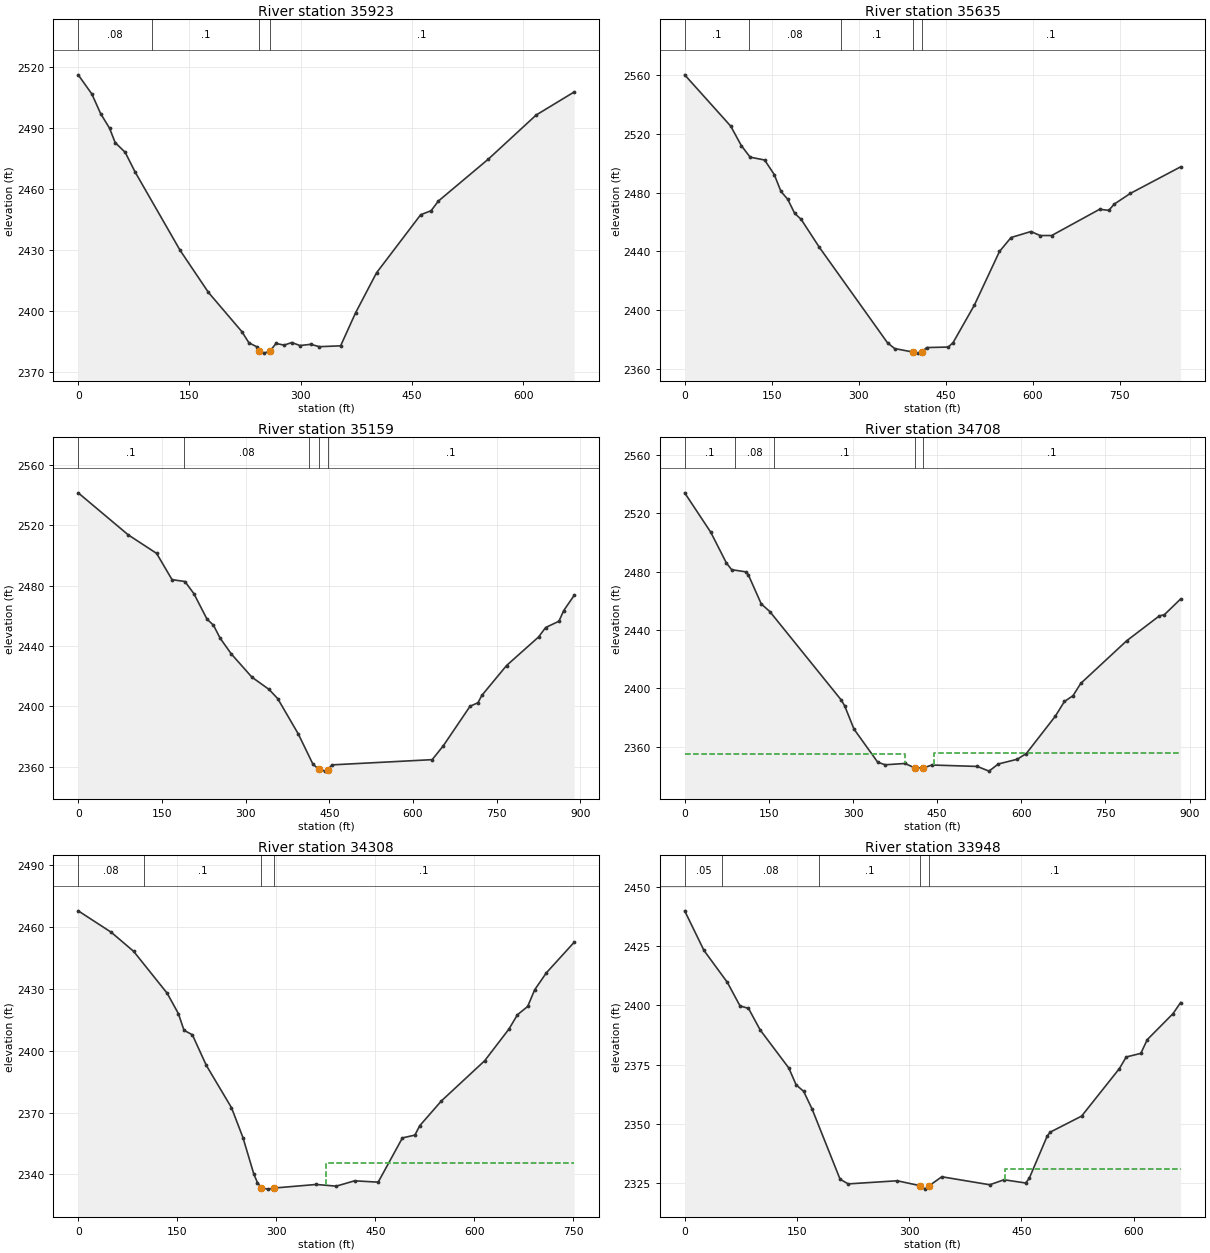
Type RM Length L Ch R = 1 ,35923   ,288.4,288.1,286.6
XS GIS Cut Line= 4
2274079.82358924665097.6669436182274281.08719938664994.650498616
2274321.14915022664961.265539588 2274605.6710566664694.158792161
#Sta/Elev= 30
       0 2516.29    18.4 2506.82    30.3 2497.11    42.2 2490.02    49.8  2482.9
    63.3  2478.1    76.8 2468.33   137.3 2429.81   175.6 2409.01   220.6  2389.7
   230.1  2384.2   240.5 2382.28  244.232380.365   250.9 2379.11   258.92380.306
   266.6 2383.87   277.6 2383.06   287.9 2384.33   298.9 2382.86   313.4 2383.45
   325.1 2382.29   353.7 2382.71   373.8 2398.93   402.1 2418.69   461.6 2447.32
   475.7 2449.31   485.4 2454.04     553  2474.8   617.3 2496.48   668.5 2507.83
#Mann= 4 ,-1,0
       0     .08       0     100      .1       0  244.23    .045       0
   258.9      .1       0
Bank Sta=244.23,258.9
XS Rating Curve= 0 ,0
Exp/Cntr(USF)=0,0
Exp/Cntr=0.3,0.1

Type RM Length L Ch R = 1 ,35635   ,473.4,476.2,475.7
XS GIS Cut Line= 4
2274131.09710576665424.6576795342274435.86841488665235.537862704
2274493.45189655665174.519236165 2274742.3077853 664845.86683818
#Sta/Elev= 30
       0 2560.22    79.4 2525.27    97.6 2512.04   112.8 2504.17   137.8 2502.21
   154.4  2492.3     166 2480.79   177.6 2475.49   189.6 2465.89   200.8 2461.79
   231.9  2442.9   349.6 2377.75   361.9 2373.82   392.92371.495     403 2370.71
   408.32371.507   417.2  2374.5   454.3 2374.85   462.6 2377.85   499.5 2403.55
   542.6 2439.94   562.5 2449.42   596.8 2453.51   612.7 2450.78   632.6  2450.8
   715.2 2468.67     731 2467.93   740.3 2472.16   768.1 2479.46   854.8 2497.57
#Mann= 5 ,-1,0
       0      .1       0     110     .08       0     270      .1       0
   392.9    .045       0   408.3      .1       0
Bank Sta=392.9,408.3
XS Rating Curve= 0 ,0
Exp/Cntr=0.3,0.1

Type RM Length L Ch R = 1 ,35159   ,451,451.2,448.7
XS GIS Cut Line= 4
2274394.53561317665770.8315558422274753.16665023665563.645344013
2274799.14620552665525.5225488432275060.30593659665202.863650385
#Sta/Elev= 30
       0 2541.51    89.7 2513.62   140.5 2501.36   168.2 2483.93   191.3 2482.69
   207.4 2474.62   230.8  2457.8   242.5 2453.69   254.2 2445.24   274.4 2434.67
   311.4 2419.25   342.1 2411.12   357.6 2405.04   394.6 2381.53   420.9 2361.45
   431.82358.029   443.1 2356.94   447.42357.967     455 2361.09   634.5 2364.55
   654.5 2373.78   702.4 2399.97   716.6 2402.32   723.5 2407.16   767.8 2426.97
   825.2  2445.9   837.9 2452.19   861.7 2456.34   870.2 2463.37     889  2473.5
#Mann= 5 ,-1,0
       0      .1       0     190     .08       0  414.18      .1       0
   431.8    .045       0   447.4      .1       0
Bank Sta=431.8,447.4
XS Rating Curve= 0 ,0
Exp/Cntr=0.3,0.1

Type RM Length L Ch R = 1 ,34708   ,396.7,399.8,404
XS GIS Cut Line= 4
2274606.20114925666087.2285851142274966.31905442 665950.02267499
2275006.18892407665906.2038684132275428.59151573665785.605421368
#Sta/Elev= 30
       0 2533.92    46.5  2506.9    74.4 2485.81    83.7 2481.26   108.5  2479.8
   113.4  2477.8   136.4 2457.86   151.9  2452.5     279 2391.97   285.2  2387.9
   301.7 2372.07   344.1 2349.31   357.4 2347.57   392.9 2348.47   409.9 2345.43
  425.612345.426   440.6 2347.41   521.6 2346.44   542.4 2343.22     559 2348.12
   592.7 2351.35   608.9 2355.28   660.6 2380.87   676.8 2390.94   692.1  2394.9
   705.9 2403.33   787.8 2432.55     846 2449.61   854.8 2450.35   883.9 2461.18
#Mann= 5 ,-1,0
       0      .1       0      90     .08       0     160      .1       0
   409.9    .045       0  425.61      .1       0
#XS Ineff= 2 , 0
          392.61 2354.67  445.06         2355.72
Permanent Ineff=
       F       F
Bank Sta=409.9,425.61
XS Rating Curve= 0 ,0
Exp/Cntr=0.3,0.1

Type RM Length L Ch R = 1 ,34308   ,362.6,360.2,352.9
XS GIS Cut Line= 4
2274856.77775549666386.9907631472275145.71403124666287.259050794
2275235.53285052666248.0401776592275473.04179105665994.491889291
#Sta/Elev= 30
       0 2467.94    50.1 2457.52      84 2448.26   134.8 2427.91   151.7 2418.06
   160.2 2409.98   172.9 2407.78     194 2392.95   232.1 2372.43   249.5  2357.9
     266 2340.17   271.5 2335.99  277.462333.562   287.1 2332.88   296.32333.398
   360.6 2335.15   390.8 2334.32   418.6 2336.92   454.3 2336.26     491 2357.74
   509.9  2359.1   517.2 2363.64   550.1 2375.71   615.6 2395.19   652.4 2410.59
   665.2 2417.51   680.7 2421.52   691.3 2429.61     709 2437.85   751.1 2452.68
#Mann= 4 ,-1,0
       0     .08       0     100      .1       0  277.46    .045       0
   296.3      .1       0
#XS Ineff= 2 , 0
                          375.07         2345.32
Permanent Ineff=
       F       F
Bank Sta=277.46,296.3
XS Rating Curve= 0 ,0
Exp/Cntr=0.3,0.1

Type RM Length L Ch R = 1 ,33948   ,340,339.6,337.6
XS GIS Cut Line= 4
2275116.62239929 666778.065457312275291.17804221666623.540789808
2275364.62495207666522.4320567522275533.45745916666268.706368138
#Sta/Elev= 30
       0 2439.94    25.8 2423.21      57 2409.75      74 2399.77    85.3 2398.75
   100.9 2389.64   139.2 2373.55     149 2366.43     159 2363.72   170.4 2356.17
   207.7  2326.6   218.6 2324.62   284.2 2325.94   315.1 2323.82   321.4 2322.41
  326.132323.697   343.7 2327.63   407.8 2324.25   426.9 2326.37   455.7    2325
   460.5 2326.93   484.5 2344.77   488.5 2346.46   530.6 2353.26   581.1 2373.34
   590.2 2378.22   609.7 2379.74   618.3 2385.54   652.7 2396.51   662.9  2401.2
#Mann= 5 ,-1,0
       0     .05       0      50     .08       0     180      .1       0
   315.1    .045       0  326.13      .1       0
#XS Ineff= 2 , 0
                          427.69         2330.93
Permanent Ineff=
       F       F
Bank Sta=315.1,326.13
XS Rating Curve= 0 ,0
Exp/Cntr(USF)=0,0
Exp/Cntr=0.3,0.1

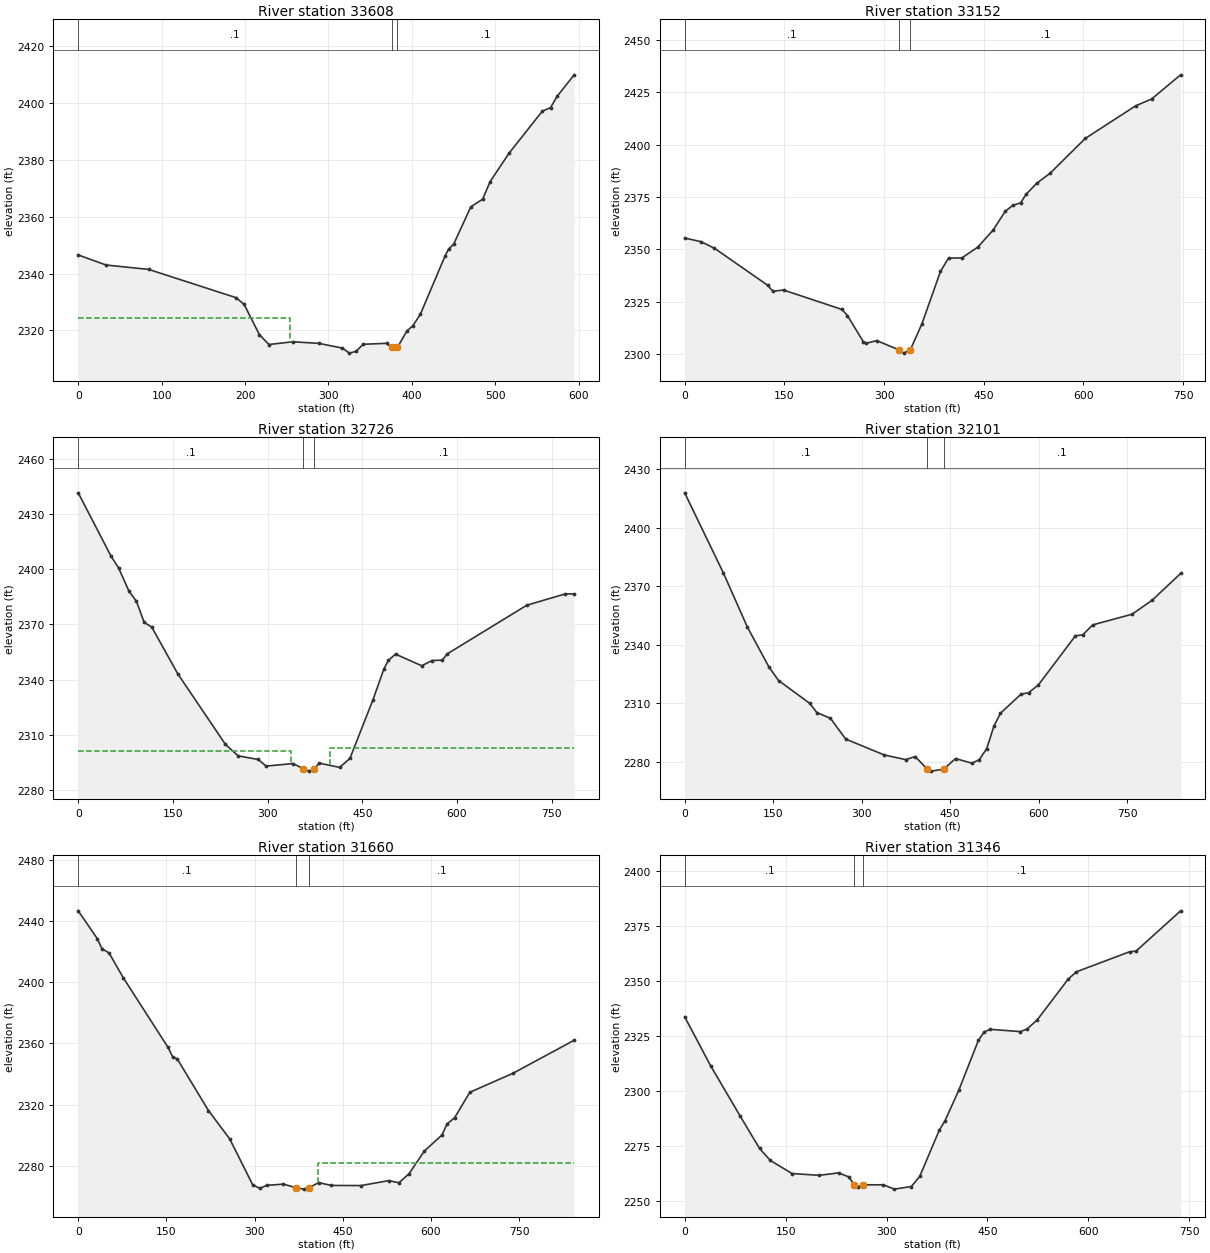
Type RM Length L Ch R = 1 ,33608   ,446.7,456.6,461.3
XS GIS Cut Line= 4
2275418.14876772666966.4770078782275604.47035579666773.230427819
2275626.46253389666632.7392948782275789.26292755666546.828974646
#Sta/Elev= 30
       0 2346.55    33.5    2343    84.4 2341.47   189.1 2331.53   198.9 2329.17
   217.3 2318.48   228.7 2315.02   257.4 2315.99   288.7 2315.42   316.9 2313.75
   325.2 2311.99   333.3 2312.63   341.7 2315.11   369.7 2315.44   375.72314.034
   382.82313.975     394 2319.75   401.3 2321.65   410.2 2325.61   439.7 2346.05
   444.1 2348.65   450.1 2350.27   470.8 2363.51   484.9 2366.16     494  2372.4
   516.6 2382.36   556.6  2397.2   566.4 2398.39   574.4 2402.44   594.7 2409.96
#Mann= 3 ,-1,0
       0      .1       0   375.7    .045       0   382.8      .1       0
#XS Ineff= 2 , 0
           254.3 2324.51
Permanent Ineff=
       F       F
Bank Sta=375.7,382.8
XS Rating Curve= 0 ,0
Exp/Cntr=0.3,0.1

Type RM Length L Ch R = 1 ,33152   ,424.2,425.7,424.5
XS GIS Cut Line= 4
2275451.67617905667045.8824776412275724.62323656667059.881972782
2275834.17363292667056.4197450242276195.55052738667019.088084595
#Sta/Elev= 30
       0 2355.38    24.5 2353.64    44.6 2350.53   124.7 2332.84   132.7 2329.94
   148.7 2330.52   236.8 2321.21   244.8 2318.34   268.9 2305.74   272.9 2305.02
   288.9 2306.35  321.842301.971   329.8 2300.35  339.592301.971     357 2314.38
   384.9 2339.42     397 2345.78   417.1 2345.88   441.2 2351.08   464.2 2359.22
   482.5 2368.24   493.5 2370.94   505.6 2372.25   513.6 2376.26   529.8  2381.6
   549.8 2386.34   602.7 2402.99   678.5 2418.58   702.6 2421.88   746.2 2433.41
#Mann= 3 ,-1,0
       0      .1       0  321.84    .045       0  339.59      .1       0
Bank Sta=321.84,339.59
XS Rating Curve= 0 ,0
Exp/Cntr=0.3,0.1

Type RM Length L Ch R = 1 ,32726   ,609.8,625,619.9
XS GIS Cut Line= 4
2275364.43031357 667432.341698882275697.31775586667470.509854361
2275752.08433275667469.4092653022276142.10280076667401.544475442
#Sta/Elev= 30
       0 2441.51    52.1 2407.04    64.2 2400.55    80.3 2388.15    92.3 2382.56
   104.4 2371.17   116.5 2368.56   157.9 2343.11   233.3 2304.83   253.4 2298.62
   285.3 2296.65   297.7 2293.06   340.7 2294.45  356.22 2291.64   365.9 2290.33
   373.9 2291.64   381.9 2294.67   414.3 2292.34   430.5 2297.29   467.1  2329.2
   484.5 2346.01   491.4 2350.48   502.7 2353.89   544.2 2347.57   560.5 2350.41
   576.7 2350.63   584.8 2354.05   710.7 2380.46   771.6  2386.6   785.7 2386.61
#Mann= 3 ,-1,0
       0      .1       0  356.22    .045       0   373.9      .1       0
#XS Ineff= 2 , 0
          337.56 2301.41  398.44         2302.69
Permanent Ineff=
       F       F
Bank Sta=356.22,373.9
XS Rating Curve= 0 ,0
Exp/Cntr=0.3,0.1

Type RM Length L Ch R = 1 ,32101   ,446.8,441,435.6
XS GIS Cut Line= 4
2275463.54519401667831.0467314252275849.22564088667899.962417455
2275954.32822628667910.5353075572276282.87791943 667811.32028661
#Sta/Elev= 30
       0 2417.98    65.7 2376.76   106.3 2349.02   142.9  2328.5   159.1  2321.6
   211.9 2309.88   224.1 2305.13   247.1 2302.19   272.9 2291.53   337.9  2283.4
   374.5 2280.97   390.7 2282.53  411.342276.052   417.5 2275.06   438.92276.051
   459.1 2281.52   486.9 2279.12   499.4 2280.99   511.9 2286.59   524.4 2298.38
   535.3 2304.81   570.4 2314.67   582.9 2315.28   599.6 2319.36   662.3 2344.55
   674.8 2345.07   691.6 2350.17   758.4 2355.64   792.7 2362.92   840.6 2376.58
#Mann= 3 ,-1,0
       0      .1       0  411.34    .045       0   438.9      .1       0
Bank Sta=411.34,438.9
XS Rating Curve= 0 ,0
Exp/Cntr=0.3,0.1

Type RM Length L Ch R = 1 ,31660   ,309.6,313.5,308.7
XS GIS Cut Line= 4
2275607.80405444668339.8189737352275936.46927459668322.605213183
2276085.93818799668271.1688020742276417.01110418668138.967522474
#Sta/Elev= 30
       0 2446.53    32.4 2428.42    40.4 2421.83    52.4 2419.07    76.5 2402.97
   152.6 2357.58   160.6 2351.35   168.6 2349.83   221.6 2316.25   257.9 2297.64
   296.8 2267.82   308.8 2265.47   320.8 2267.44   348.9 2268.25   370.9 2265.89
   383.8 2264.98   392.3 2265.88   409.2 2269.22   430.7 2267.38   481.1 2267.31
   528.4 2270.54   545.6 2269.13   562.8 2275.01   588.9 2289.83   618.8 2300.28
   627.4 2307.47   640.3 2311.53   666.2 2328.15   739.8 2340.58   843.7  2362.1
#Mann= 3 ,-1,0
       0      .1       0   370.9    .045       0   392.3      .1       0
#XS Ineff= 2 , 0
                          407.95         2282.05
Permanent Ineff=
       F       F
Bank Sta=370.9,392.3
XS Rating Curve= 0 ,0
Exp/Cntr=0.3,0.1

Type RM Length L Ch R = 1 ,31346   ,318.9,321.1,319.7
XS GIS Cut Line= 3
2275849.73337191668594.846550611 2276059.5816858668568.350551382
2276565.12535108668424.212315578
#Sta/Elev= 30
       0 2333.65    38.7 2311.29    82.4  2288.5   111.3  2273.7   127.4 2268.22
   159.7 2262.27     200 2261.47   228.8 2262.57   243.7 2260.77   252.3 2257.17
   257.9 2256.32   265.62257.138   295.3 2257.15   311.7 2255.18   336.9 2256.37
   349.4 2260.96   378.5 2282.06   386.8 2286.21   407.6 2300.31   436.7 2323.01
   445.1 2326.72   454.1 2327.97   499.1 2326.92   509.1 2328.15   524.1 2332.27
   569.8 2350.73   582.3 2354.16   661.3 2363.28   670.9 2363.58   737.2 2381.93
#Mann= 3 ,-1,0
       0      .1       0   252.3    .045       0   265.6      .1       0
Bank Sta=252.3,265.6
XS Rating Curve= 0 ,0
Exp/Cntr(USF)=0,0
Exp/Cntr=0.3,0.1

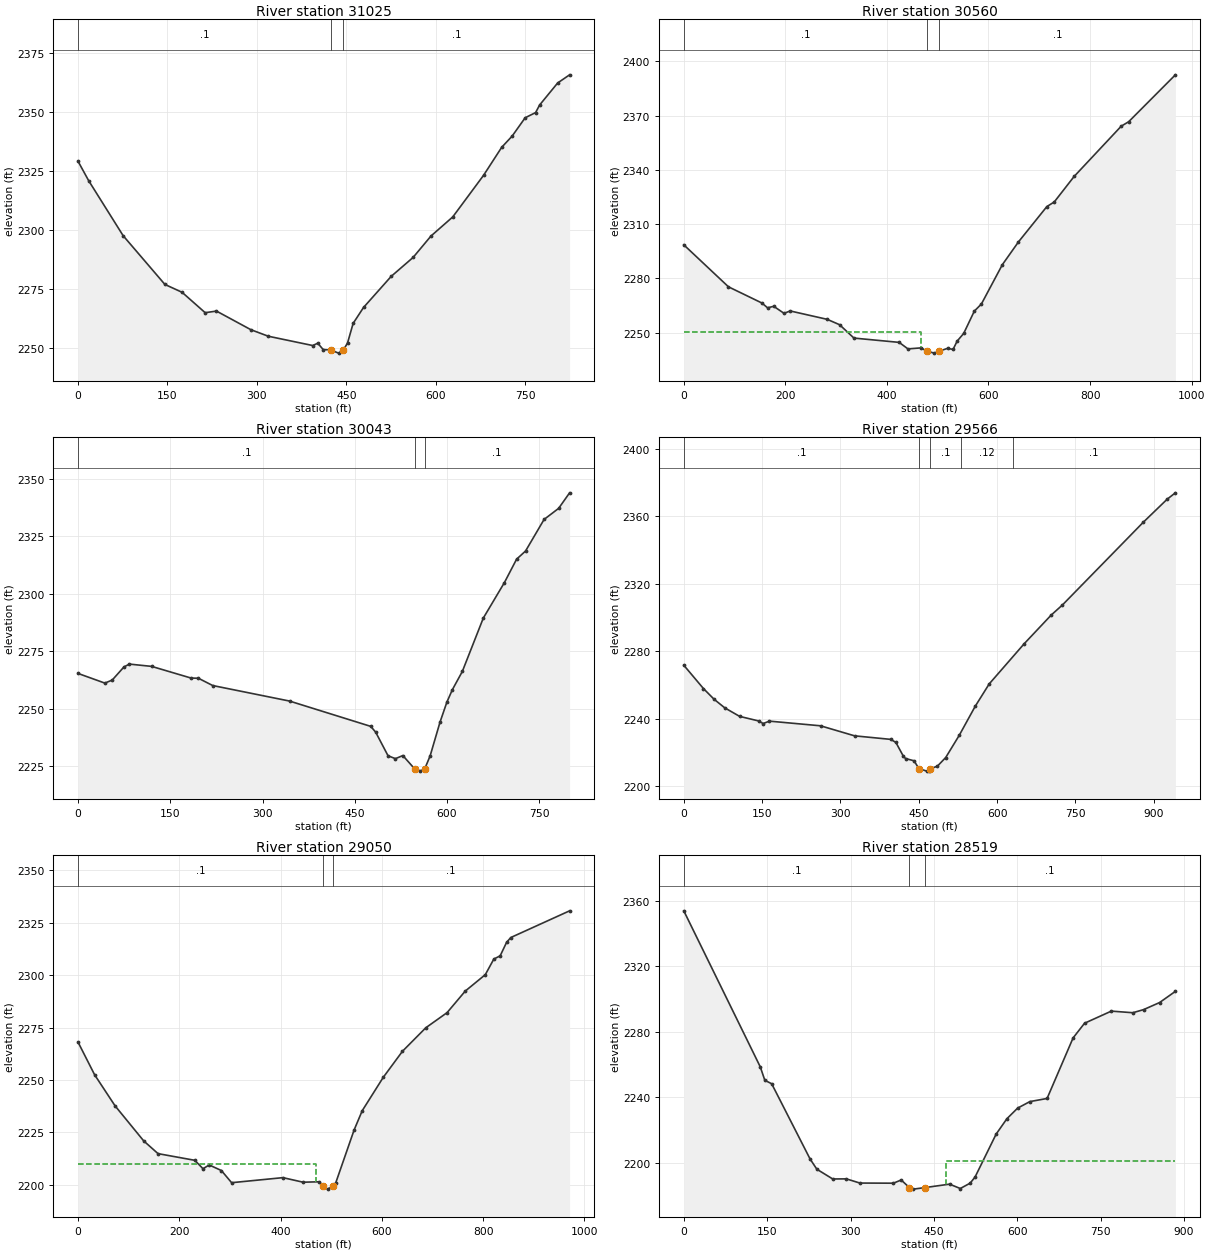
Type RM Length L Ch R = 1 ,31025   ,465.9,465.7,464.9
XS GIS Cut Line= 4
2275834.62286642668757.0854304862276191.32831253668844.225262512
2276283.26215735668812.0050986012276612.28546326668667.041377978
#Sta/Elev= 30
       0 2329.12    17.9 2320.86    75.7 2297.56   145.7 2276.91   174.5 2273.58
   213.2 2264.94   232.2 2265.62   289.8 2257.74     319 2254.97   393.5 2251.03
     402 2252.01   411.1 2249.31   423.6 2249.16   436.9 2247.81     445 2249.15
   451.9 2252.11   461.3 2260.41   478.7 2267.15   525.1 2280.33   561.8 2288.34
   591.8 2297.42   628.3 2305.51     680 2323.15   710.4 2335.02   727.9 2339.76
   749.7 2347.52   767.2 2349.71   773.9 2352.91   804.2 2362.26   824.2 2365.71
#Mann= 3 ,-1,0
       0      .1       0   423.6    .045       0     445      .1       0
Bank Sta=423.6,445
XS Rating Curve= 0 ,0
Exp/Cntr=0.3,0.1

Type RM Length L Ch R = 1 ,30560   ,517,516.5,519.3
XS GIS Cut Line= 4
 2275961.2130476669330.1300356482276380.77127764669263.929622883
2276467.67410837669227.6735065592276835.54660228668970.039046224
#Sta/Elev= 30
       0 2298.59      88 2275.38   153.8 2266.44     165 2263.78   177.1 2264.62
   197.4 2260.73   209.5 2262.05   282.4 2257.42   306.7 2254.46   335.1 2247.06
   424.1 2244.69   441.4 2241.09   467.4 2241.65  478.642239.845   493.4 2238.75
   502.9 2239.82   519.5  2241.4   530.2 2240.79   538.3  2245.4   551.2 2249.65
   572.1 2261.96     586 2265.88   627.3 2287.62   658.9 2300.16   714.9 2319.71
   729.5 2322.26   768.6 2336.35   861.4 2364.14     876 2366.58     968  2392.5
#Mann= 3 ,-1,0
       0      .1       0  478.64    .045       0   502.9      .1       0
#XS Ineff= 2 , 0
          467.63 2250.48
Permanent Ineff=
       F       F
Bank Sta=478.64,502.9
XS Rating Curve= 0 ,0
Exp/Cntr=0.3,0.1

Type RM Length L Ch R = 1 ,30043   ,476.4,477.2,480.7
XS GIS Cut Line= 3
2276160.53985603669681.0129763552276664.19206097669661.260686378
2276957.46884964669626.668143668
#Sta/Elev= 30
       0  2265.3    43.7 2261.09    55.7 2262.43    74.8 2268.14    83.7 2269.35
   119.7 2268.36   183.8 2263.29   195.8  2263.2   219.1 2260.03   343.9 2253.29
     476 2242.28     484 2239.77   504.1 2229.51   516.1 2228.25   528.2  2229.6
   547.3 2223.83   556.4 2222.83  563.732223.799   572.6 2229.51   588.6 2244.11
   599.8 2252.84   608.7 2258.23   624.9 2266.16     659 2289.36   693.3 2304.78
   713.1 2314.95   727.7 2318.51   757.8 2332.23   781.5 2337.05   799.3  2343.8
#Mann= 3 ,-1,0
       0      .1       0   547.3    .045       0  563.73      .1       0
Bank Sta=547.3,563.73
XS Rating Curve= 0 ,0
Exp/Cntr=0.3,0.1

Type RM Length L Ch R = 1 ,29566   ,518.4,516.3,512.8
XS GIS Cut Line= 4
     2276203.166 670042.231241542276613.30663305 670121.76432124
2276714.31980388 670136.65621542 2277131.6689825670078.016983664
#Sta/Elev= 30
       0  2271.7    37.7 2257.84    58.1  2251.5    78.5 2246.42     107 2241.36
   143.6 2238.64   151.8 2237.13     164 2238.55   261.8 2235.79     327 2229.84
   396.3 2227.74   406.1 2225.94   420.7 2217.61   424.7 2216.39   440.9 2215.04
  450.162210.438   465.2 2208.92   469.2 2209.04  472.372210.438   485.4  2211.8
   501.5 2216.97   527.4 2230.12   558.1  2247.4   584.8 2260.61   652.1 2284.54
   703.5 2301.42   724.8 2307.34   879.8 2356.43   925.7 2370.14   941.3 2373.88
#Mann= 5 ,-1,0
       0      .1       0  450.16    .045       0  472.37      .1       0
  529.89     .12       0  629.89      .1       0
Bank Sta=450.16,472.37
XS Rating Curve= 0 ,0
Exp/Cntr=0.3,0.1

Type RM Length L Ch R = 1 ,29050   ,534.9,530.5,523.6
XS GIS Cut Line= 4
     2276219.626       670582.332276634.77877018670638.690549239
  2276783.871894670622.3838283142277166.87819914670501.367556204
#Sta/Elev= 30
       0 2268.14    32.8 2252.53    73.2  2237.7   129.7 2220.98     158  2214.9
   230.6 2211.71   246.8  2207.7   259.1 2209.49   283.1 2206.83   303.3 2201.03
   404.6 2203.44   444.5 2201.26   476.7 2201.47  484.182199.284   492.8 2197.96
  502.792199.282   508.9 2200.97   545.1 2226.15   561.2 2235.39   602.8 2251.34
   640.6 2263.73   686.7 2274.95   728.7 2282.17   764.6 2292.46   804.2  2300.3
     821 2307.74   833.5 2309.27   846.1 2315.66   854.5 2318.01   970.6 2330.75
#Mann= 3 ,-1,0
       0      .1       0  484.18    .045       0  502.79      .1       0
#XS Ineff= 2 , 0
          469.88 2210.08
Permanent Ineff=
       F       F
Bank Sta=484.18,502.79
XS Rating Curve= 0 ,0
Exp/Cntr=0.3,0.1

Type RM Length L Ch R = 1 ,28519   ,467.4,472.8,473.1
XS GIS Cut Line= 4
2276264.90944808671218.6500350062276586.31974663671157.819384994
2276769.97958934671070.8213933722277063.74112135670873.379810969
#Sta/Elev= 30
       0 2353.87   137.6 2258.49   145.8 2250.27   158.1 2248.18   227.2 2202.17
   239.4 2195.92   267.9 2189.97   292.4 2190.03   316.8 2187.47     377 2187.39
   391.1 2189.34  405.832184.704   413.1 2183.76  433.432184.689   478.1  2186.8
   497.4 2184.14   515.1 2187.41   523.9 2191.12   561.9 2217.41   581.2 2226.78
   600.5 2233.27   622.5 2237.26   653.5 2239.18   700.3 2276.19   720.9 2285.16
   769.1 2292.57   807.7 2291.58   827.1 2293.48   855.9 2297.81   884.3 2304.64
#Mann= 3 ,-1,0
       0      .1       0  405.83    .045       0  433.43      .1       0
#XS Ineff= 2 , 0
                          472.12         2201.09
Permanent Ineff=
       F       F
Bank Sta=405.83,433.43
XS Rating Curve= 0 ,0
Exp/Cntr=0.3,0.1

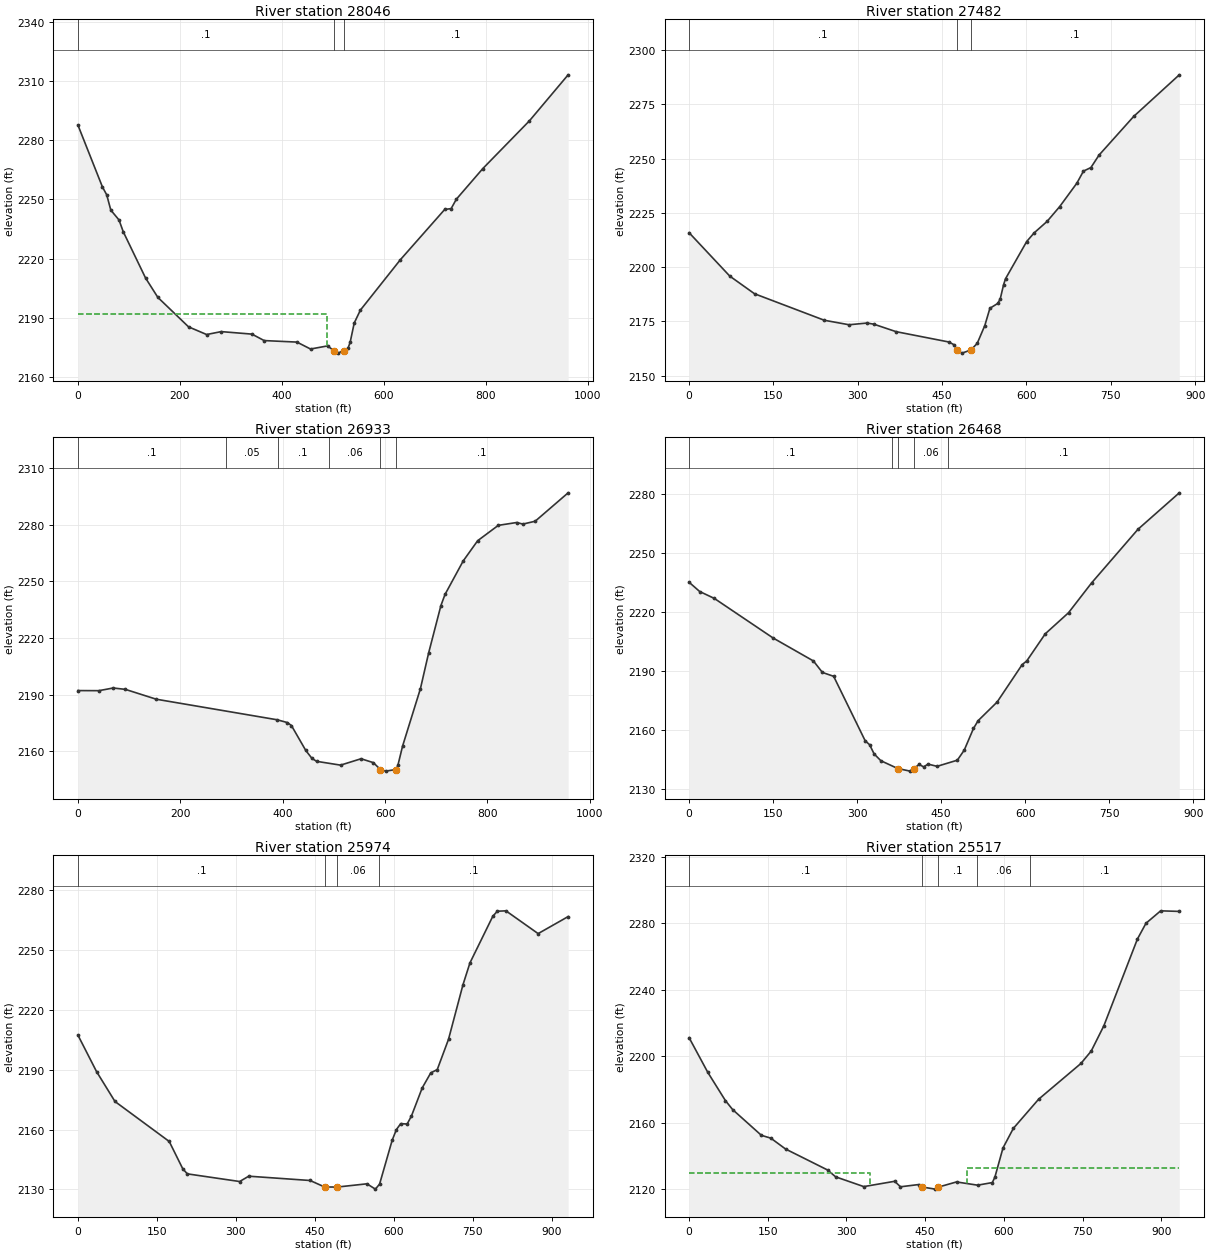
Type RM Length L Ch R = 1 ,28046   ,566.1,564.3,558.6
XS GIS Cut Line= 4
2276407.87462634671520.5565557142276799.80257616671489.502764164
2276972.32619059671473.9929990172277353.32455224671368.280077632
#Sta/Elev= 30
       0 2287.65      48 2256.37    56.5 2252.31    64.5  2244.6    80.6 2239.59
    88.9 2233.65   132.7 2210.19   156.8 2200.38     217 2185.46   252.5 2181.56
   281.2 2183.04   341.4 2181.77   365.4  2178.5   429.7 2177.73   456.4 2174.22
   489.9 2175.81  501.672173.434     510 2172.14  521.972173.434   530.1 2174.74
   534.1 2177.59   542.1 2187.39   554.2 2193.93   632.6 2219.44   719.6  2244.9
   732.3 2245.36   742.4 2250.08   794.5 2265.65   885.9 2289.82   961.8 2313.11
#Mann= 3 ,-1,0
       0      .1       0  501.67    .045       0  521.97      .1       0
#XS Ineff= 2 , 0
          488.74 2192.16
Permanent Ineff=
       F       F
Bank Sta=501.67,521.97
XS Rating Curve= 0 ,0
Exp/Cntr=0.3,0.1

Type RM Length L Ch R = 1 ,27482   ,539.5,548.6,555.3
XS GIS Cut Line= 4
2276587.73154727672017.9599900532277030.33830077672021.463025878
2277109.37841099671980.145091625 2277403.7047463671809.949393046
#Sta/Elev= 30
       0 2215.91    72.4  2195.9   116.4 2187.78   240.5 2175.57   284.5  2173.5
   316.5 2174.29   328.5 2173.77   368.1 2170.32     462 2165.56   471.8 2164.21
  476.462161.854   485.3 2160.43  500.972161.852   512.4 2164.91   525.9 2173.12
     535 2181.09   548.9 2183.32   553.3 2185.34   559.4 2192.02   562.8 2194.71
   600.4 2211.83   613.6 2215.81   636.7 2221.11     659 2227.89   689.6 2238.71
   701.4 2244.28   714.6 2245.91   729.1 2251.66   790.7 2269.46   871.8 2288.63
#Mann= 3 ,-1,0
       0      .1       0  476.46    .045       0  500.97      .1       0
Bank Sta=476.46,500.97
XS Rating Curve= 0 ,0
Exp/Cntr=0.3,0.1

Type RM Length L Ch R = 1 ,26933   ,467.7,465.6,466.3
XS GIS Cut Line= 4
2276727.24190053672442.5901846632277289.61425136672432.637190528
2277378.27408429672431.9295765552277684.59598504672424.889940145
#Sta/Elev= 30
       0 2192.14    40.9 2192.09    68.9 2193.51    92.7 2192.78     153 2187.57
     389 2176.69     409 2175.22     417 2173.65     445 2160.47     457 2156.27
   466.2 2154.69     513 2152.67     553 2156.05     577    2154  590.892150.352
     601  2149.5  621.572150.353     625 2152.58   634.1 2162.72     669 2193.17
     685 2212.03     709 2237.14     717 2243.02   752.6 2260.79   780.8 2271.48
   821.1 2279.61   857.1 2281.12   869.1 2280.28   893.1 2281.79   957.5 2296.83
#Mann= 6 ,-1,0
       0      .1       0     290     .05       0     390      .1       0
     490     .06       0  590.89    .045       0  621.57      .1       0
Bank Sta=590.89,621.57
XS Rating Curve= 0 ,0
Exp/Cntr=0.3,0.1

Type RM Length L Ch R = 1 ,26468   ,492.3,494,494.5
XS GIS Cut Line= 4
 2276854.9875817672857.3398492882277206.00947118672885.365373349
2277335.56448625672875.0869584972277715.44233636672775.621227485
#Sta/Elev= 30
       0 2235.31    18.9  2230.6    45.1 2227.08   149.7 2207.02   221.9  2195.3
   237.9 2189.48     258  2187.5   314.2 2154.77   322.2 2152.72   330.2 2148.06
   342.3  2144.6  372.392140.645   394.4 2139.32  401.132140.645   410.5 2142.72
   418.5  2141.5   426.5 2142.87   442.6 2141.76   478.7 2144.88     491 2149.97
   507.5    2161   515.8 2164.96   549.7 2174.42   594.4 2193.45   602.6 2195.32
   635.7 2209.13   677.1  2219.8   718.4    2235   801.1 2262.23   874.8 2280.75
#Mann= 5 ,-1,0
       0      .1       0  362.14     .06       0  372.39    .045       0
  401.13     .06       0  462.14      .1       0
Bank Sta=372.39,401.13
XS Rating Curve= 0 ,0
Exp/Cntr=0.3,0.1

Type RM Length L Ch R = 1 ,25974   ,448.3,457.3,455.5
XS GIS Cut Line= 4
 2276875.4199825673182.6800023342277284.40262305673348.789770033
2277446.21721816673350.0804309662277768.02267211 673285.34149825
#Sta/Elev= 30
       0  2207.4    35.4  2189.1    70.4 2174.11   173.5 2154.05   199.4 2140.25
     208  2137.8   307.3 2133.96   324.6 2136.63   441.2 2134.47  468.822131.208
   493.2 2131.19   549.2 2132.81   565.2 2130.14   573.2 2132.65   597.2 2154.71
   605.2 2160.03   613.4 2162.99   625.6  2162.8   633.8 2166.85   654.2 2180.91
   670.5 2188.47   682.8 2190.11   704.2  2205.3   731.7 2232.69   744.9 2243.62
   788.5  2267.1     797 2269.56   813.3 2269.76   874.5 2258.33   931.5 2266.87
#Mann= 4 ,-1,0
       0      .1       0  468.82    .045       0   493.2     .06       0
  571.43      .1       0
Bank Sta=468.82,493.2
XS Rating Curve= 0 ,0
Exp/Cntr=0.3,0.1

Type RM Length L Ch R = 1 ,25517   ,519.5,511.8,497.9
XS GIS Cut Line= 4
2276894.87329872673619.506103851 2277237.8852204 673756.21150807
2277385.84147222673782.9092121342277799.52387562673751.278388115
#Sta/Elev= 30
       0 2211.18    35.8 2190.21    69.3 2173.27    83.2 2167.82   137.8 2152.38
   155.8 2150.67   183.9 2144.14   264.1 2131.49   279.4 2127.38     333  2121.5
   391.9  2124.7     403 2121.39   437.5 2122.73  444.812121.233   469.1 2119.98
   475.4 2121.22   509.8 2124.31     550 2122.36   578.1 2123.93     583 2127.23
   598.4 2144.76   618.2 2156.58   666.4 2174.13     747 2195.64   766.6 2203.11
   790.7 2218.33   854.7 2270.58     871 2280.06     899 2287.55   934.5  2287.2
#Mann= 5 ,-1,0
       0      .1       0  444.81    .045       0   475.4      .1       0
   549.6     .06       0   649.6      .1       0
#XS Ineff= 2 , 0
          345.55 2129.69  529.77         2132.94
Permanent Ineff=
       F       F
Bank Sta=444.81,475.4
XS Rating Curve= 0 ,0
Exp/Cntr=0.3,0.1