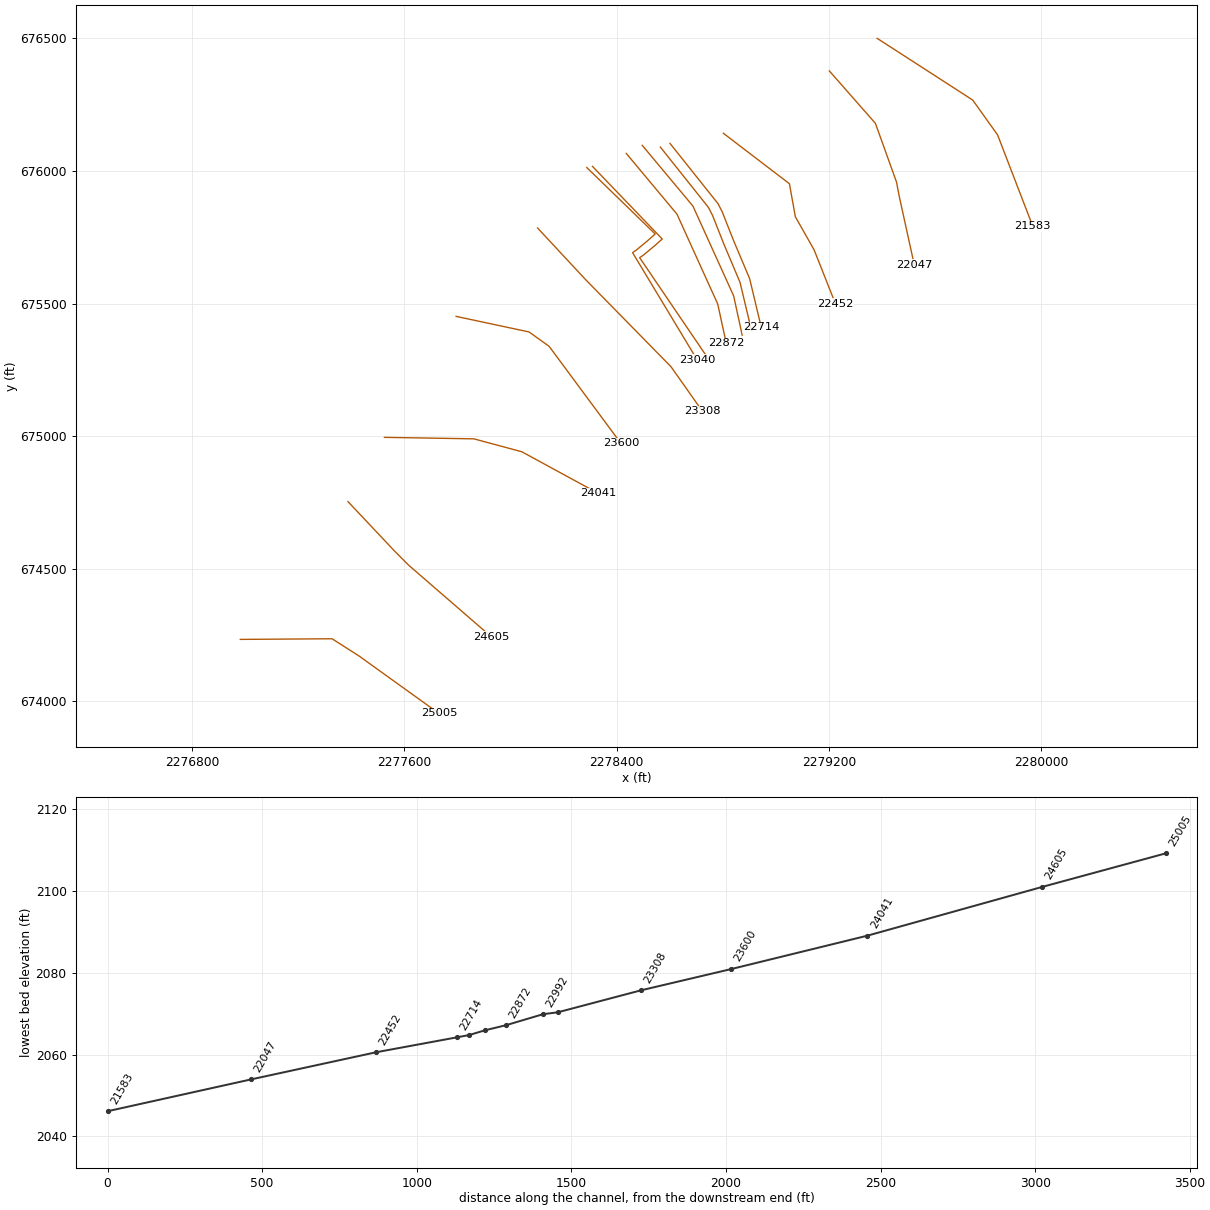
HEC-RAS study BEAVCK1.prj: BEAVCK1

--- BEAVCK1.g01 (geometry) --- (continued)

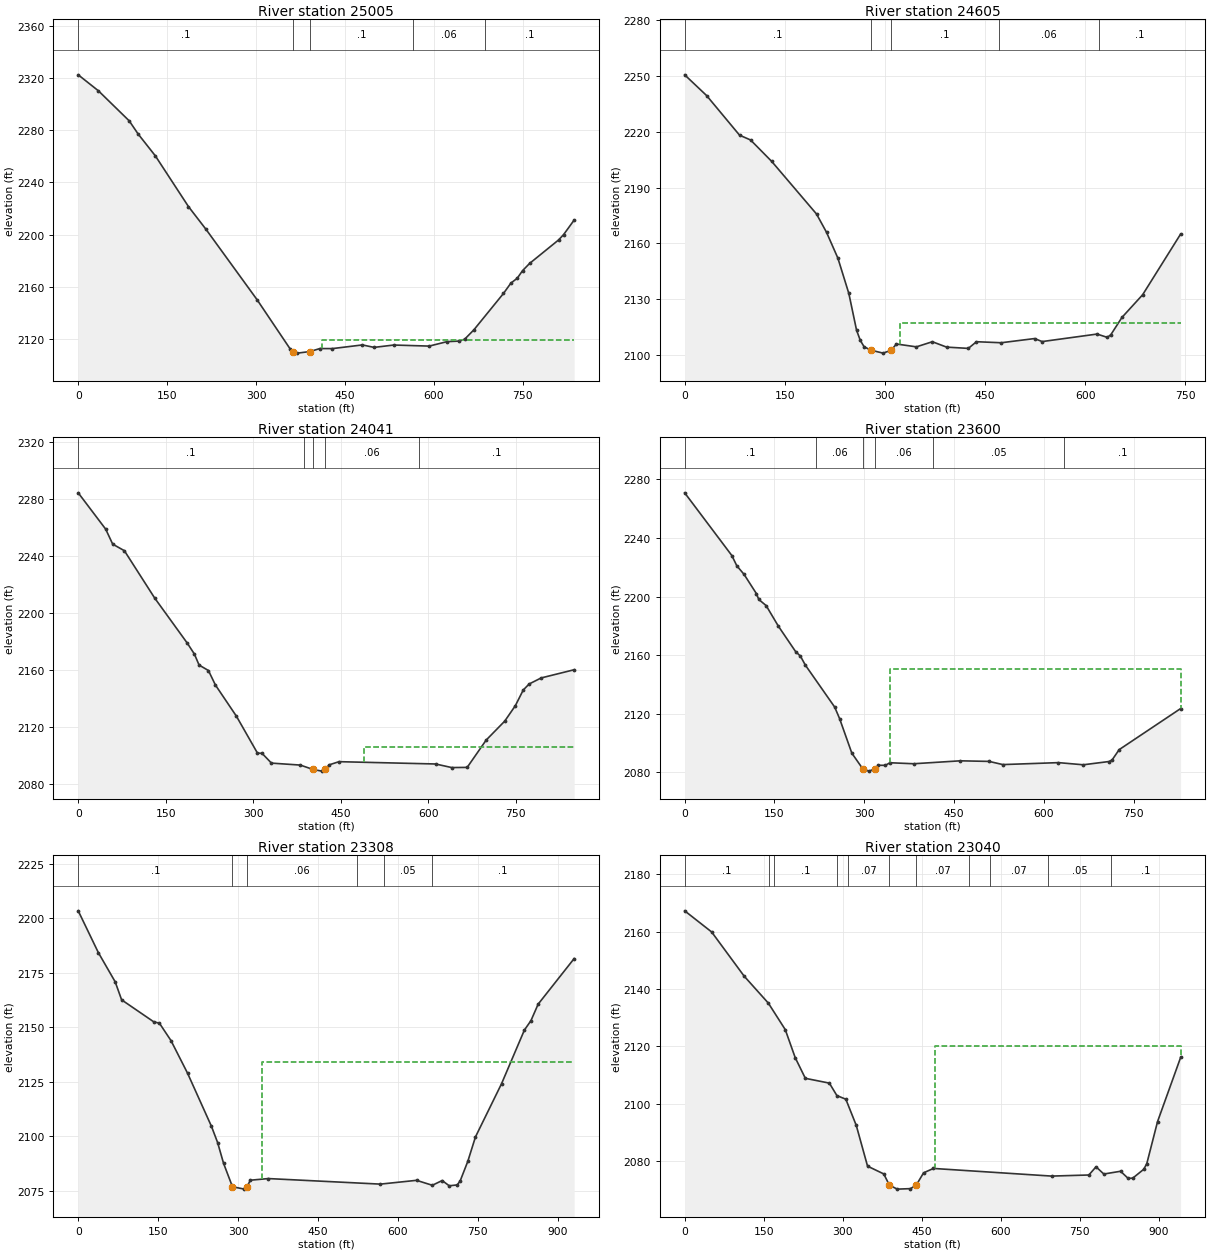
Type RM Length L Ch R = 1 ,25005   ,402.5,399.8,396
XS GIS Cut Line= 4
 2276982.0875606674233.3186573992277327.69349654674235.753562946
2277428.91927875 674171.058875712277730.19271085673954.347702684
#Sta/Elev= 30
       0 2322.37    34.1 2310.12    86.1 2287.08   101.2 2276.97   130.1 2260.32
   186.1 2221.38   215.8 2203.87   302.1 2149.86   357.8 2112.21  362.192110.308
   369.9  2109.1  391.022110.309   407.9 2112.61   428.9 2112.57   479.6 2115.38
   499.3  2113.5   532.5  2115.3   592.3 2114.49   622.5 2117.91   642.2 2118.31
   652.1 2119.76   667.6  2126.9   717.6 2154.82   730.2 2162.79   740.8 2166.45
   749.8 2172.28   761.7 2177.82   810.5 2195.79   819.1 2199.93   836.9 2211.08
#Mann= 5 ,-1,0
       0      .1       0  362.19    .045       0  391.02      .1       0
  565.75     .06       0  685.75      .1       0
#XS Ineff= 2 , 0
                          410.78            2119
Permanent Ineff=
       F       F
Bank Sta=362.19,391.02
XS Rating Curve= 0 ,0
Exp/Cntr=0.3,0.1

Type RM Length L Ch R = 1 ,24605   ,557.3,564.1,568.7
XS GIS Cut Line= 4
2277387.66618156674753.0394961492277561.53890927674568.257318212
2277616.07106585674513.3639991322277927.17998011674243.584980106
#Sta/Elev= 30
       0 2250.67    32.8 2239.53    82.2 2218.19    98.7 2215.61   130.4 2204.06
   197.5 2175.77   212.5 2165.91   229.5 2152.02   245.9 2133.02   257.5 2113.19
   263.1 2107.74   268.8 2104.29  279.482102.442   297.2  2100.9  309.182102.441
   317.2 2105.81   347.1 2104.28     371 2107.03   392.4 2104.13   424.9 2103.45
   437.1 2107.04   474.2 2106.49   524.1 2108.74   535.5 2107.12   617.7 2111.16
     633 2109.39   638.3 2110.77     655 2120.11     686 2132.31   742.9 2164.97
#Mann= 5 ,-1,0
       0      .1       0  279.48    .045       0  309.18      .1       0
   471.1     .06       0   621.1      .1       0
#XS Ineff= 2 , 0
                          323.12         2117.26
Permanent Ineff=
       F       F
Bank Sta=279.48,309.18
XS Rating Curve= 0 ,0
Exp/Cntr=0.3,0.1

Type RM Length L Ch R = 1 ,24041   ,444.3,441.4,437
XS GIS Cut Line= 4
2277525.11003316674995.280299099 2277861.9944909674989.682328345
2278042.64591674674940.9781167472278328.73637647674785.101354362
#Sta/Elev= 30
       0 2284.56    47.1 2259.03    59.1  2248.5    79.1 2243.89     131 2210.65
   187.1 2178.83   199.1 2171.25   207.1 2163.55   223.1 2159.72   235.1 2149.53
   271.1 2127.61   307.1 2101.72   315.1 2101.49   331.1 2094.65   380.6 2093.27
  402.472090.188   417.4 2089.02  422.762090.186   430.3 2093.48   446.9 2095.66
   612.3 2094.04     640 2091.53   666.5 2091.64     699 2110.82   730.8 2124.13
     749 2134.98   762.6 2146.03   772.7 2150.25   793.3  2154.5   849.8 2160.26
#Mann= 5 ,-1,0
       0      .1       0  386.93     .06       0  402.47    .045       0
  422.76     .06       0  584.03      .1       0
#XS Ineff= 2 , 0
                          490.24         2106.24
Permanent Ineff=
       F       F
Bank Sta=402.47,422.76
XS Rating Curve= 0 ,0
Exp/Cntr=0.3,0.1

Type RM Length L Ch R = 1 ,23600   ,291.3,291.1,288.4
XS GIS Cut Line= 4
 2277795.0918098675451.4694679112278069.77118059675392.802967338
 2278145.4325108675338.5789705782278415.58941424674973.179708284
#Sta/Elev= 30
       0 2270.86    78.8 2228.03      87  2221.1    99.3 2215.13   119.7 2202.11
   123.8 2198.05   136.1 2193.86   156.5 2179.82   185.2 2162.52   193.3 2159.39
   201.5 2153.28   250.6 2124.56   258.8 2116.67   279.2 2093.14  297.522082.369
   307.7 2080.85  318.112082.367   323.2 2084.86   335.2  2084.8   342.9 2086.57
   382.6 2085.89   460.3 2087.89   508.5 2087.49   531.4 2085.32   624.4 2086.65
   665.8 2085.18     709 2087.42     714 2088.53   725.8 2095.54   828.4 2123.56
#Mann= 6 ,-1,0
       0      .1       0     220     .06       0  297.52    .045       0
  318.11     .06       0  413.96     .05       0  633.96      .1       0
#XS Ineff= 2 , 0
                          342.24         2150.59
Permanent Ineff=
       F       F
Bank Sta=297.52,318.11
XS Rating Curve= 0 ,0
Exp/Cntr=0.3,0.1

Type RM Length L Ch R = 1 ,23308   ,292.9,268.8,233.7
XS GIS Cut Line= 4
2278101.84612584675784.8982831692278281.47596015675591.582366248
 2278604.8096619 675261.405623192278722.85212444675093.751111171
#Sta/Elev= 30
       0 2203.48    37.8 2184.29    69.4 2170.88    81.5  2162.6   141.6 2152.54
   152.5 2151.86   174.1 2143.92   205.2 2128.95   250.2 2104.49   261.7 2097.07
   272.9 2087.51  289.592076.764     312 2075.67  316.872076.768   323.2 2079.76
   356.8 2080.52   567.3 2077.97   635.2 2079.71   664.8 2077.44   683.3 2079.61
   696.5 2077.21   711.6  2077.6   717.2 2079.49   731.5 2088.47   745.8 2099.64
   794.8 2124.09   837.7 2148.73     850 2153.05   863.5 2160.62   931.1 2181.56
#Mann= 6 ,-1,0
       0      .1       0  289.59    .045       0  316.87     .06       0
  523.89      .1       0  573.89     .05       0  663.89      .1       0
#XS Ineff= 2 , 0
                           344.4         2134.08
Permanent Ineff=
       F       F
Bank Sta=289.59,316.87
XS Rating Curve= 0 ,0
Exp/Cntr(USF)=0,0
Exp/Cntr=0.3,0.1

Type RM Length L Ch R = 1 ,23040   ,40.2,48,59.7
XS GIS Cut Line= 6
 2278287.2112709676012.8704750092278545.02992127675762.231818705
2278514.83707632675735.4520859742278473.27389143675700.933508693
2278459.88913697675691.7755188022278702.95662907675287.927120923
#Sta/Elev= 30
       0 2167.21    51.2 2159.85   112.9 2144.47   158.9 2135.06     191 2125.84
   209.8 2116.11   229.1 2108.89   274.7 2107.22     289 2102.88     306 2101.61
   325.8 2092.49   347.2 2078.31     378  2075.6   388.62071.716   403.5 2070.31
   428.7 2070.48   439.72071.716   453.6 2075.99   472.3 2077.51   696.7 2074.85
   767.4 2075.23     781 2078.08   795.8 2075.57   827.6 2076.53   842.1 2074.03
   850.8 2074.15   871.6 2077.22   877.4  2079.2   897.8 2093.82   941.6 2116.15
#Mann= 11 ,-1,0
       0      .1       0     160     .06       0     170      .1       0
     290     .05       0     310     .07       0   388.6    .045       0
   439.7     .07       0   540.2     .06       0   580.2     .07       0
   690.2     .05       0   810.2      .1       0
#XS Ineff= 2 , 0
                          475.09            2120
Permanent Ineff=
       F       F
Bank Sta=388.6,439.7
XS Rating Curve= 0 ,0
Exp/Cntr=0.3,0.1

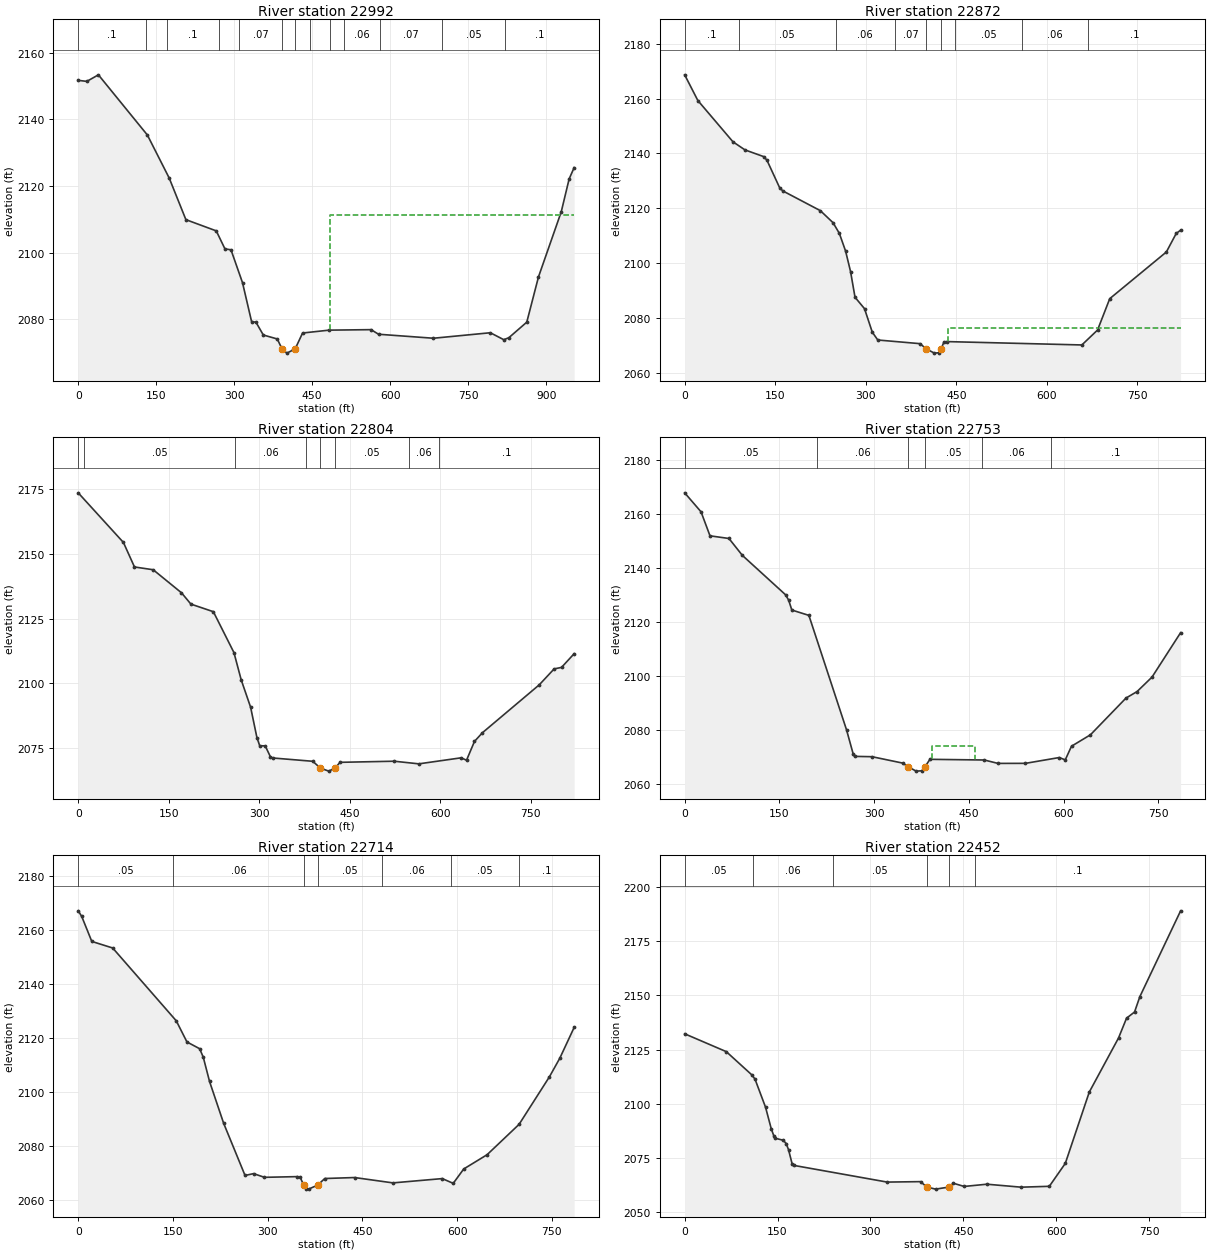
Type RM Length L Ch R = 1 ,22992   ,108,119.8,137.2
XS GIS Cut Line= 6
2278308.73664712676017.1547079992278571.60623181675743.281753792
2278541.41338687675716.5020210612278499.85020198675681.983443781
2278486.46544752 675672.825453892278746.70611633675289.180793317
#Sta/Elev= 30
       0 2151.75    16.6 2151.44    38.8 2153.41     133 2135.34     175 2122.41
   207.1 2109.92   265.5 2106.55   282.2 2101.14   293.8 2100.87     316 2090.98
   333.4 2079.33   341.9 2079.11     356 2075.28   382.9 2074.09  391.882071.119
   401.4 2069.84  417.292071.119   431.5 2075.88   482.5 2076.74   563.2 2076.89
   577.6 2075.51   683.2 2074.31   792.6 2075.96   818.5 2073.87   828.2 2074.47
   862.7 2079.14   885.2 2092.73     929 2112.29   944.2 2122.17   953.8 2125.56
#Mann= 13 ,-1,0
       0      .1       0     130     .06       0     170      .1       0
     270     .05       0     310     .07       0  391.88    .045       0
  417.29     .07       0  446.02     .06       0  484.03     .07       0
  510.24     .06       0  580.24     .07       0  700.24     .05       0
  820.24      .1       0
#XS Ineff= 2 , 0
                           485.2         2111.33
Permanent Ineff=
       F       F
Bank Sta=391.88,417.29
XS Rating Curve= 0 ,0
Exp/Cntr=0.3,0.1

Type RM Length L Ch R = 1 ,22872   ,67.6,67.9,67.6
XS GIS Cut Line= 4
2278436.19176131676065.9234690312278627.14186778675836.957017662
2278780.48056631675498.4928383532278812.79699996675350.041097773
#Sta/Elev= 30
       0 2168.68    21.8 2159.31      80 2144.24    99.9 2141.29   131.2 2138.82
   136.4 2137.48   157.2 2127.55   162.4 2126.35   224.8 2119.12   245.8 2114.73
   256.2 2110.86   266.6 2104.36   274.8 2096.91   282.2 2087.53   297.9 2083.37
   310.8 2074.79   319.9 2071.94   390.1  2070.6  399.852068.748   413.6 2067.15
   420.9 2067.29  424.772068.748   429.6 2071.22     434 2071.36     658 2070.13
     684 2075.58   704.2 2087.02     798 2104.05   814.3 2110.81   821.6 2112.01
#Mann= 9 ,-1,0
       0      .1       0      90     .05       0     250     .06       0
  348.14     .07       0  399.85    .045       0  424.77     .07       0
  448.14     .05       0  558.14     .06       0  668.14      .1       0
#XS Ineff= 2 , 0
                          436.38         2076.32
Permanent Ineff=
       F       F
Bank Sta=399.85,424.77
XS Rating Curve= 0 ,0
Exp/Cntr(USF)=0,0
Exp/Cntr=0.3,0.1

Type RM Length L Ch R = 1 ,22804   ,52.2,51.3,51.3
XS GIS Cut Line= 4
2278496.20591138676096.5463691272278687.15601784675867.579917758
2278840.49471637675529.1157384492278872.81115002675380.663997869
#Sta/Elev= 30
       0  2173.7    74.9 2154.48    93.2 2144.98   124.2 2143.91   171.1 2134.98
   186.7  2130.6   223.9 2127.66     258 2111.82     270 2101.27   285.6 2090.67
   296.1 2078.86   300.7 2075.73   309.8  2075.7   318.3 2071.52   321.9 2071.01
   388.6 2069.72  401.222067.079     415 2065.91  425.48 2067.08   433.7 2069.32
   523.5 2069.75   564.3 2068.73   634.5 2071.07   643.3 2070.12   656.5 2077.43
   669.6 2080.77   763.8 2099.34   788.4  2105.5   800.7 2106.09   821.6  2111.4
#Mann= 8 ,-1,0
       0      .1       0      10     .05       0     260     .06       0
  378.14     .05       0  401.22    .045       0  425.48     .05       0
  548.14     .06       0  598.14      .1       0
Bank Sta=401.22,425.48
XS Rating Curve= 0 ,0
Exp/Cntr(USF)=0,0
Exp/Cntr=0.3,0.1

Type RM Length L Ch R = 1 ,22753   ,39,38.8,38.8
XS GIS Cut Line= 6
2278564.52362695676089.9392875912278745.44809453675862.647242892
2278760.90395357675832.6446929922278803.63485797675724.453679715
2278864.54912595675579.8959392862278908.18919853675397.153135348
#Sta/Elev= 30
       0 2167.78    25.9 2160.75    40.1 2151.86    70.1 2150.88    91.4 2144.61
   159.7 2130.05   164.6 2128.09   169.7 2124.39   196.7 2122.41   256.4 2079.98
   266.8 2071.15   269.2 2070.21   296.7 2070.09   345.1 2067.73  354.212066.332
   366.5 2064.75   375.4 2064.87  380.462066.334   388.4 2069.12   474.5 2068.87
   496.2 2067.61   539.7 2067.63   593.2 2069.78   602.7 2068.92   612.6 2073.97
   642.6  2078.2   698.9  2091.8   716.4  2094.2   740.1 2099.56   785.4 2116.01
#Mann= 6 ,-1,0
       0     .05       0     210     .06       0  354.21    .045       0
  380.46     .05       0  470.61     .06       0  580.61      .1       0
#XS Ineff= 1 ,-1
  391.81  460.43 2073.91
Permanent Ineff=
       F
Bank Sta=354.21,380.46
XS Rating Curve= 0 ,0
Exp/Cntr(USF)=0,0
Exp/Cntr=0.3,0.1

Type RM Length L Ch R = 1 ,22714   ,263.3,261.9,257.9
XS GIS Cut Line= 6
2278600.75756618 676103.919311392278781.68203376675876.627266691
 2278797.1378928 675846.624716792278839.86879721675738.433703514
2278900.78306519675593.8759630852278944.42313777675411.133159147
#Sta/Elev= 30
       0 2167.24     5.5  2165.2    21.5 2155.91    54.6 2153.48   155.3 2126.51
   172.2 2118.69   192.3 2116.19     198 2113.08     208 2104.05   230.3 2088.59
   264.2 2069.26   277.7 2069.94   294.9 2068.57   347.2 2068.83   351.5 2068.59
   357.12065.695   360.1 2064.32   364.8  2064.2   379.22065.696   390.5 2068.13
   437.7 2068.49   498.4 2066.51   576.5  2068.1   593.9 2066.34   610.5 2071.66
   647.5 2076.94   698.2 2088.19   746.2 2105.77   762.7 2112.68   785.4 2124.07
#Mann= 7 ,-1,0
       0     .05       0     150     .06       0   357.1    .045       0
   379.2     .05       0  480.61     .06       0  590.61     .05       0
  697.47      .1       0
Bank Sta=357.1,379.2
XS Rating Curve= 0 ,0
Exp/Cntr(USF)=0,0
Exp/Cntr=0.3,0.1

Type RM Length L Ch R = 1 ,22452   ,403.8,404.5,404.2
XS GIS Cut Line= 5
2278801.92482854676142.0207420222279050.66194017675951.838017075
2279072.99879303675827.3594583492279143.66000147 675702.42153208
2279223.72307357675500.021972105
#Sta/Elev= 30
       0 2132.25    67.2 2124.01   108.6 2113.24   113.6 2111.29   130.6 2098.34
   139.7 2088.51   143.8 2085.25   146.3 2084.03   159.1 2083.11     164 2081.56
   167.7 2078.72   173.4 2072.34   176.3  2071.5     327  2063.8   380.8 2064.01
  391.052061.507   405.2 2060.55     427 2061.51   433.7 2063.28   451.3 2061.79
     488 2062.82   543.3 2061.45   588.8 2061.85   614.6 2072.43   653.3 2105.34
   700.6 2130.35   713.5 2139.46   726.4  2142.3     735 2149.41   800.8 2189.01
#Mann= 6 ,-1,0
       0     .05       0     110     .06       0     240     .05       0
  391.05    .045       0     427     .05       0  469.58      .1       0
Bank Sta=391.05,427
XS Rating Curve= 0 ,0
Exp/Cntr=0.3,0.1

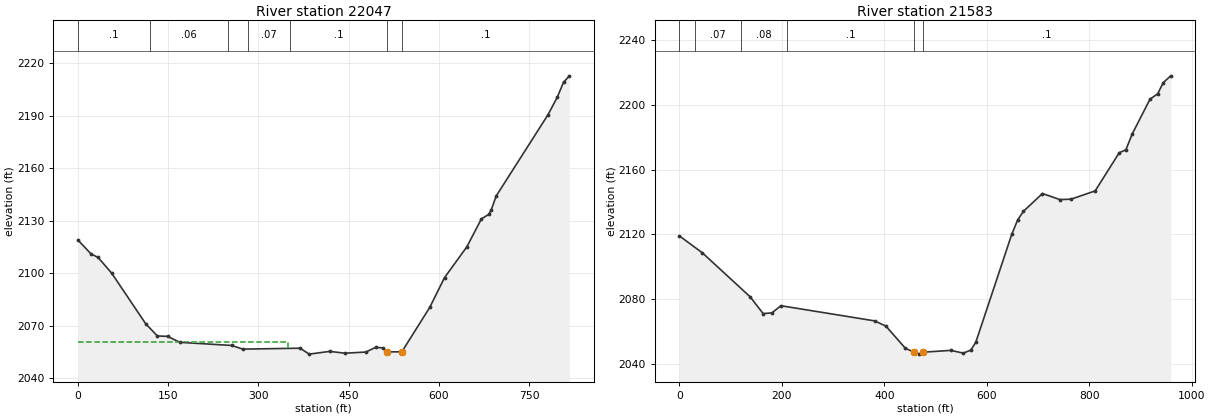
Type RM Length L Ch R = 1 ,22047   ,459.2,464,469.5
XS GIS Cut Line= 5
2279201.08255722 676377.180306242279374.58390426676179.504866831
2279454.19511199 675957.830617232279463.86941588 675906.64601448
2279520.91493368675646.349018195
#Sta/Elev= 30
       0 2119.06      22 2111.06    33.4 2109.16      56 2100.19   112.7 2071.23
     132  2064.3     149 2064.06   169.4 2060.65   255.5 2058.88     274 2056.78
   369.3  2057.3   384.5 2053.92   418.5 2055.49     444 2054.45   478.7 2055.11
     495  2057.8   507.4 2057.46  513.422055.222   538.5 2055.22   584.9 2080.57
   609.5 2097.59   646.6 2115.17   670.9 2131.19   683.2 2133.76   687.3 2136.39
   695.5 2144.27   781.5 2190.58   797.3 2200.86   807.4 2209.16   817.1 2212.88
#Mann= 7 ,-1,0
       0      .1       0     120     .06       0     250     .05       0
  283.02     .07       0  353.02      .1       0  513.42    .045       0
   538.5      .1       0
#XS Ineff= 2 , 0
          350.07 2060.95
Permanent Ineff=
       F       F
Bank Sta=513.42,538.5
XS Rating Curve= 0 ,0
Exp/Cntr=0.3,0.1

Type RM Length L Ch R = 1 ,21583   ,456,465.2,463.6
XS GIS Cut Line= 4
2279381.15914119676500.0672088672279741.13029127676267.344684641
2279834.82533863676136.0479413472279967.42056943675791.396707118
#Sta/Elev= 30
       0  2119.1    44.8 2108.66   137.9 2081.58   163.4 2071.17   180.7 2071.61
   198.1 2076.03   381.1 2066.66   403.2 2063.43   441.1 2049.76   458.2 2047.37
   468.3 2046.15   475.2 2047.34   529.9 2048.46   554.2 2046.78   568.9 2048.63
   578.7 2053.56   648.7 2120.01   660.5 2129.07   671.7 2134.31   708.7 2145.24
     743  2141.5   764.5 2141.77   811.6 2146.87   858.7 2170.45   871.6 2172.26
   884.1  2182.1   918.7 2203.48   933.7 2206.78   944.5 2213.68   959.2 2217.88
#Mann= 6 ,-1,0
       0      .1       0      30     .07       0     120     .08       0
     210      .1       0   458.2    .045       0   475.2      .1       0
Bank Sta=458.2,475.2
XS Rating Curve= 0 ,0
Exp/Cntr=0.3,0.1