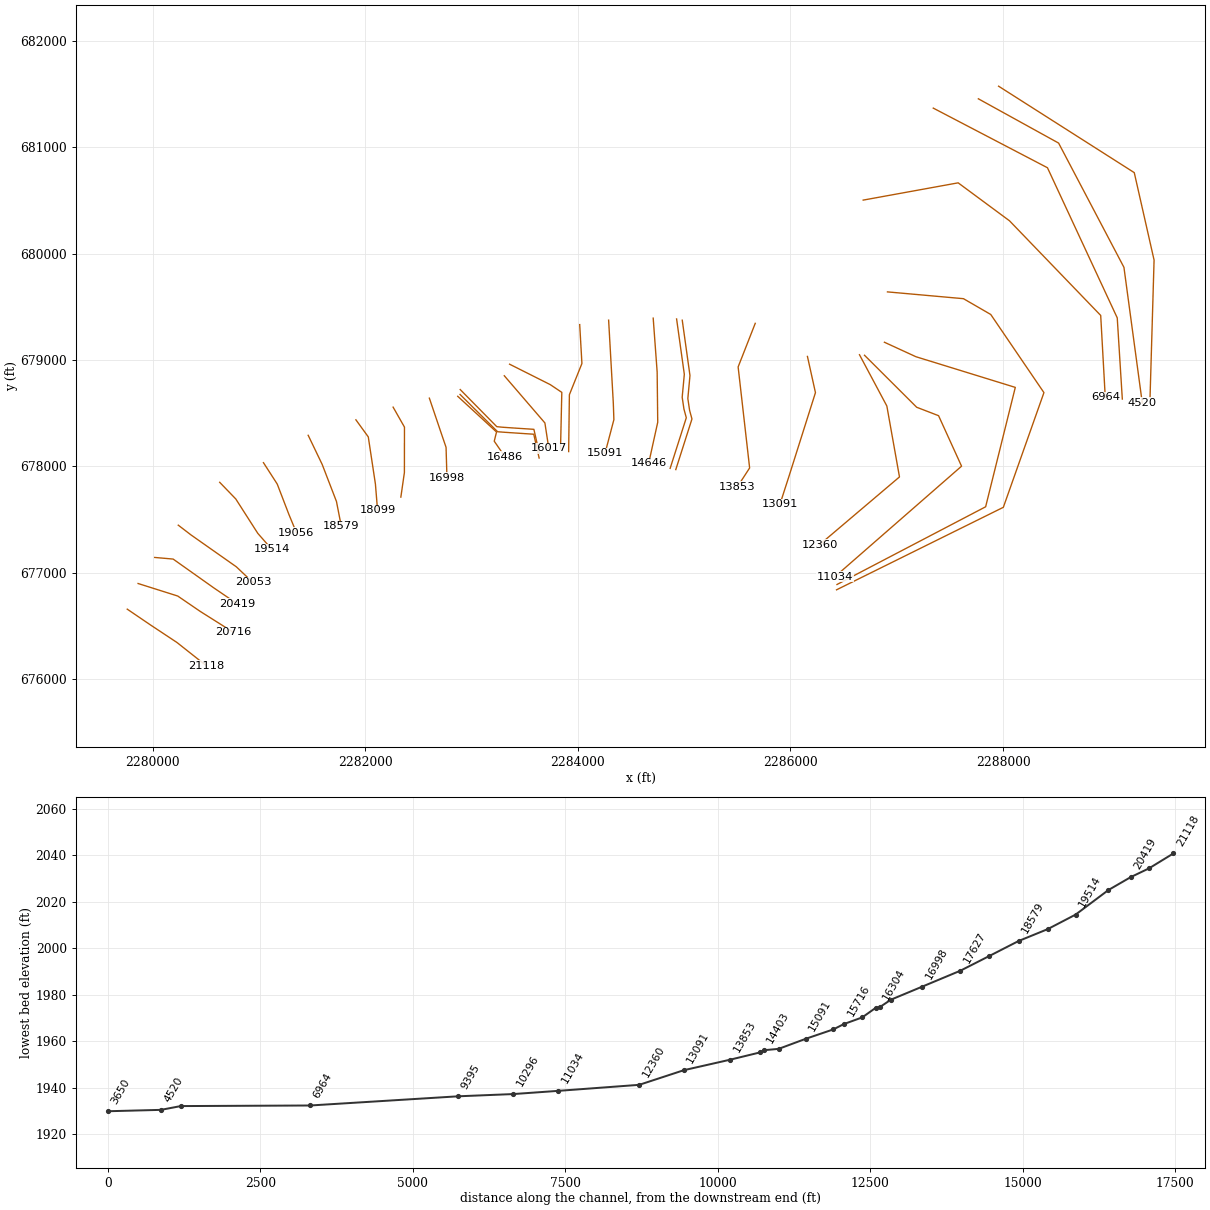
HEC-RAS study BEAVCK1.prj: BEAVCK1

--- BEAVCK1.g01 (geometry) --- (continued)

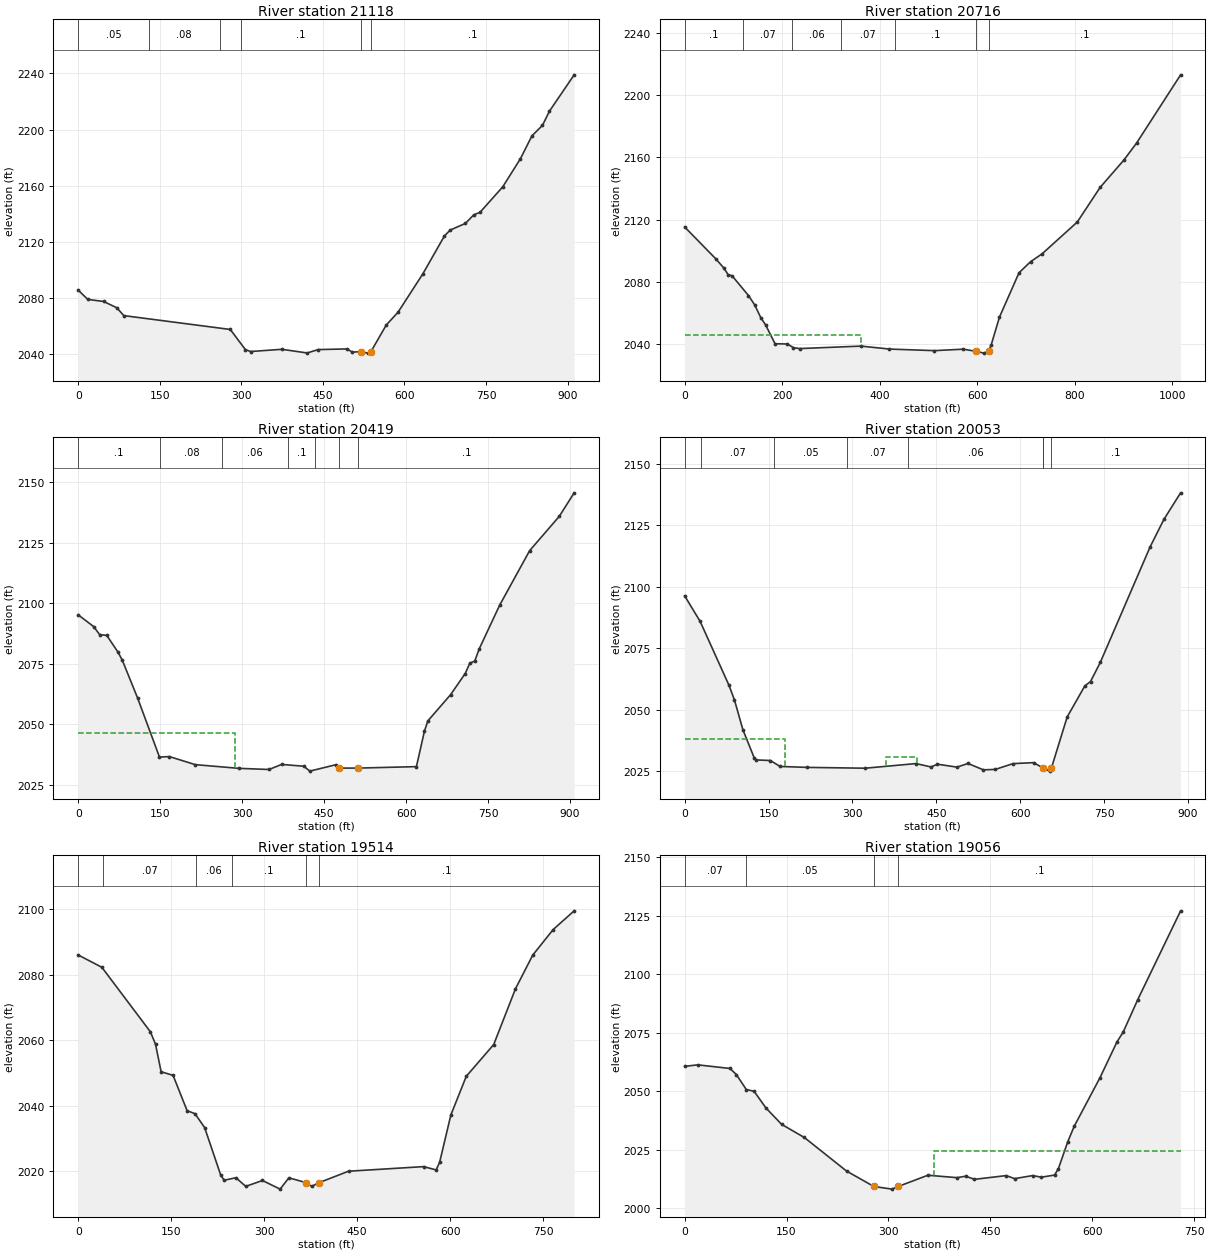
Type RM Length L Ch R = 1 ,21118   ,398.7,401.6,401
XS GIS Cut Line= 4
2279761.62400391676655.1294577452279984.53742355676503.732658774
2280229.13489505676341.7609410032280503.10758323676125.045819248
#Sta/Elev= 30
       0 2085.69    17.6 2079.04    46.6  2077.6    70.8 2073.14    83.9 2067.51
   279.7 2057.64   307.4 2043.34     317 2041.94   374.6 2043.51   421.1  2040.9
   441.3 2043.31   494.5 2043.78   504.1 2041.52   519.3  2041.8   532.9 2040.79
  538.312041.788   566.7 2060.86   588.2 2069.88   633.8 2097.19   673.6 2124.25
     684 2128.39   712.1 2133.17   727.7 2139.32   739.1 2141.07   780.9 2159.25
   813.2 2179.13   834.6 2195.58   853.9 2202.99   866.8 2213.16   912.2 2239.01
#Mann= 6 ,-1,0
       0     .05       0     130     .08       0     260     .05       0
  299.46      .1       0   519.3    .045       0  538.31      .1       0
Bank Sta=519.3,538.31
XS Rating Curve= 0 ,0
Exp/Cntr=0.3,0.1

Type RM Length L Ch R = 1 ,20716   ,297.7,297.8,292.3
XS GIS Cut Line= 4
2279863.43504794676896.5552306312280236.41625904676778.786478205
2280449.01092057  676633.47457772280760.40576933676437.163389871
#Sta/Elev= 30
       0 2115.36    63.7 2094.94    80.5 2088.93    88.9  2084.8    97.3 2083.98
   130.8 2071.34   143.6  2065.3     156 2057.14   165.9 2052.48   185.3 2040.36
   210.5 2040.22   223.1 2037.83   235.7 2037.26   361.5 2038.85   419.9 2036.95
     512 2035.93   571.2 2036.88   596.5 2035.53   613.7 2034.34  623.052035.615
   628.3  2039.5   645.4 2057.48   685.5 2085.97   709.1 2093.06   732.8 2098.12
   804.9 2118.54   851.7 2140.77   900.6  2158.4   926.7 2169.37  1016.8  2213.1
#Mann= 7 ,-1,0
       0      .1       0     120     .07       0     220     .06       0
     320     .07       0  431.13      .1       0   596.5    .045       0
  623.05      .1       0
#XS Ineff= 2 , 0
          360.98 2045.88
Permanent Ineff=
       F       F
Bank Sta=596.5,623.05
XS Rating Curve= 0 ,0
Exp/Cntr=0.3,0.1

Type RM Length L Ch R = 1 ,20419   ,371.2,365.6,356.4
XS GIS Cut Line= 4
2280020.02779271677141.7599775272280193.24227579677126.517103016
2280578.47128617676853.5310776792280794.64296105676706.645196026
#Sta/Elev= 30
       0 2095.24    28.3 2090.38    39.1  2087.1    52.3 2086.72    72.4 2079.95
    80.5 2076.58   108.6 2060.87   148.7  2036.4   166.8 2036.62   214.2 2033.28
   294.6 2031.74   349.2 2031.28   372.1 2033.37   412.8 2032.63   423.7  2030.6
   471.6 2033.26  477.692031.849   512.7 2031.86   618.8 2032.46   633.4 2047.07
   639.7 2051.37   681.3 2062.21     708 2070.95   716.6 2075.28   725.5 2076.13
   733.9 2081.27   771.3 2099.33     826 2121.81   880.2 2135.99   907.4 2145.71
#Mann= 7 ,-1,0
       0      .1       0     150     .08       0  263.88     .06       0
  383.88      .1       0  433.88     .07       0  477.69    .045       0
   512.7      .1       0
#XS Ineff= 2 , 0
          287.09 2046.43
Permanent Ineff=
       F       F
Bank Sta=477.69,512.7
XS Rating Curve= 0 ,0
Exp/Cntr(USF)=0,0
Exp/Cntr=0.3,0.1

Type RM Length L Ch R = 1 ,20053   ,542.8,539,530
XS GIS Cut Line= 4
2280241.51711099677445.3704609382280360.60596455  677354.0910153
2280787.51055175677053.8821824892280943.71739563676906.703993709
#Sta/Elev= 30
       0 2096.34    27.7 2085.92    79.2 2059.96      89 2053.99   104.1 2041.86
   124.3 2030.46   127.6 2029.61   153.3 2029.37   170.5 2026.95   219.3 2026.57
   322.7 2026.24   413.6 2028.12   440.4 2026.75   451.9 2027.86   486.9 2026.68
   506.5 2028.16   534.1 2025.57   555.4 2025.75   586.8  2028.1   623.9 2028.51
  640.232026.359   652.3 2025.05   655.7 2026.35   683.8 2047.08   715.4 2059.73
   725.5 2061.47     743 2069.27   832.2 2116.33   856.8 2127.48   886.6 2138.25
#Mann= 8 ,-1,0
       0      .1       0      30     .07       0  160.05     .05       0
  290.05     .07       0  400.05     .06       0  640.05      .1       0
  640.23    .045       0   655.7      .1       0
#XS Ineff= 2 ,-1
 -169.17  179.622038.156     360  415.392030.842
Permanent Ineff=
       F       F
Bank Sta=640.23,655.7
XS Rating Curve= 0 ,0
Exp/Cntr=0.3,0.1

Type RM Length L Ch R = 1 ,19514   ,459,458,453.6
XS GIS Cut Line= 4
2280631.27286234677848.6006555732280782.26964286677692.403864276
2280989.76092518677368.2601187582281120.25886917677219.815296986
#Sta/Elev= 30
       0 2086.02    38.1 2082.27   116.4 2062.55   124.7 2058.72   133.7 2050.34
     153 2049.23   175.6 2038.44   188.4 2037.51   203.9 2033.26   229.7 2018.82
   235.3 2017.17   254.3 2017.94   270.2  2015.3   297.1  2017.1   325.6 2014.46
   339.8 2017.92  367.342016.452   376.6  2015.3  388.482016.443   435.9 2019.93
   556.9 2021.34   577.3 2020.33   582.9 2022.71     601 2037.14   625.8 2048.93
   670.1 2058.66   705.2  2075.7     733 2085.98     766 2093.81   799.8 2099.52
#Mann= 6 ,-1,0
       0     .06       0      40     .07       0     190     .06       0
  247.25      .1       0  367.34    .045       0  388.48      .1       0
Bank Sta=367.34,388.48
XS Rating Curve= 0 ,0
Exp/Cntr=0.3,0.1

Type RM Length L Ch R = 1 ,19056   ,478.1,477,476.2
XS GIS Cut Line= 4
2281042.94567165678033.3148010532281172.60813729677831.915429241
2281281.51154016677548.2415852432281352.91568271677375.495612481
#Sta/Elev= 30
       0 2060.61    19.2 2061.27    66.8 2059.72    76.2 2057.09    90.7 2050.74
   102.3 2049.96   119.6 2042.88   142.8 2035.85   176.2 2030.25   238.3 2015.93
   278.5 2009.34   305.3  2008.2   314.6 2009.35   358.1 2014.13     401  2013.1
   413.8 2013.72   426.7 2012.38   473.5 2013.98   485.9 2012.68   512.4 2013.99
   525.2  2013.3   544.7  2014.2   550.4    2017     564 2028.35   573.6 2035.04
   611.6  2055.8   636.6 2071.08   645.8 2075.31   667.2 2089.14   730.3 2127.04
#Mann= 4 ,-1,0
       0     .07       0      90     .05       0   278.5    .045       0
   314.6      .1       0
#XS Ineff= 2 , 0
                          367.08         2024.58
Permanent Ineff=
       F       F
Bank Sta=278.5,314.6
XS Rating Curve= 0 ,0
Exp/Cntr=0.3,0.1

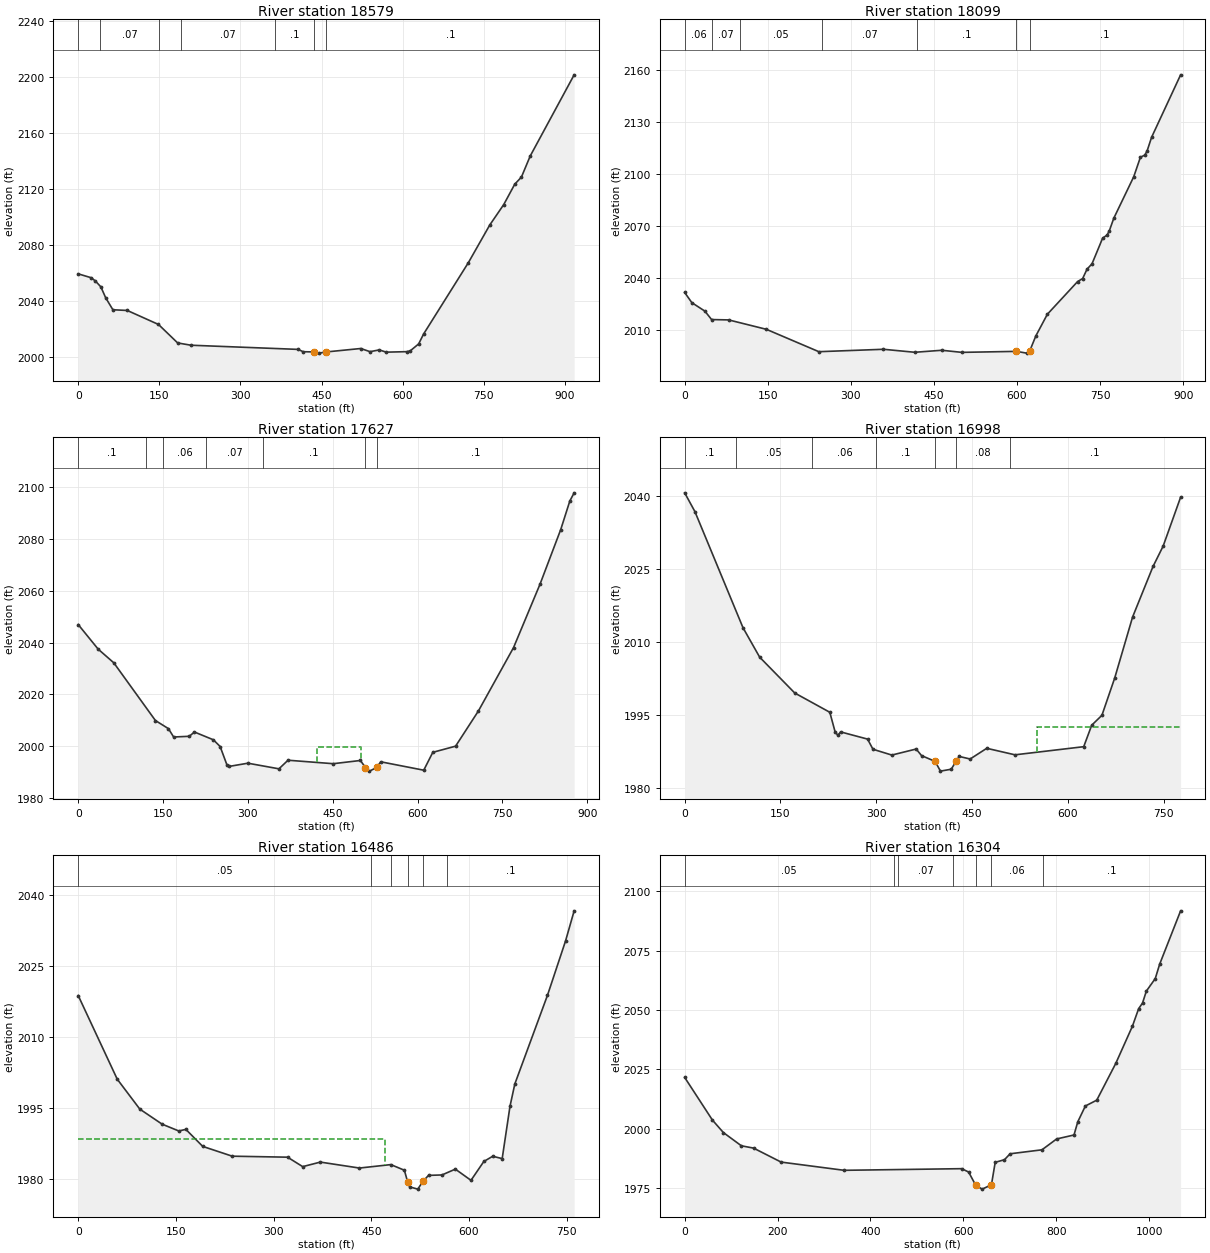
Type RM Length L Ch R = 1 ,18579   ,476.3,480.1,471.9
XS GIS Cut Line= 4
     2281463.658      678290.9372281595.30185375 678016.86685309
2281729.56702977677668.595852376     2281775.538      677433.451
#Sta/Elev= 30
       0 2059.56    24.1 2056.78    31.7 2054.49    41.9 2050.28    50.8  2042.5
    64.1 2033.98    90.7 2033.48   148.4 2023.51   183.9 2010.34   208.5 2008.72
   406.6 2005.75   415.9 2004.09   436.6 2003.94   445.2 2003.09  458.77 2003.94
   522.3 2006.38   539.5 2004.13   556.6 2005.39   569.5 2003.78   608.1 2004.14
   613.9 2004.72   629.4 2009.65   638.6 2016.74   721.5 2067.63   760.8  2094.3
   786.8 2108.95   807.1 2123.42   819.4 2128.47   835.7 2143.51   916.9 2201.31
#Mann= 7 ,-1,0
       0      .1       0      40     .07       0     150      .1       0
     190     .07       0  364.05      .1       0   436.6    .045       0
  458.77      .1       0
Bank Sta=436.6,458.77
XS Rating Curve= 0 ,0
Exp/Cntr=0.3,0.1

Type RM Length L Ch R = 1 ,18099   ,471.1,472,469.6
XS GIS Cut Line= 4
2281912.59044397678436.5373319072282029.08237116678275.635034692
2282096.17611208677831.5912022112282116.29294611677584.797763043
#Sta/Elev= 30
       0 2031.66    12.9 2025.79    36.5 2020.88    48.6 2016.02    79.4 2015.82
   147.4  2010.4   242.2 1997.47   358.9 1998.86   415.5 1997.13   464.1 1998.29
   500.5 1997.08  599.011997.654   617.2 1996.64  622.541997.619     634 2006.61
   654.7 2019.08   709.3 2037.95   718.4 2039.69   726.4 2045.16   735.3 2048.19
   754.5 2063.02   762.5 2064.83   766.5 2067.19   774.6 2074.49   810.7 2098.51
   822.7 2109.74   830.7 2111.01   834.8 2113.39   842.9 2121.28   895.3 2157.34
#Mann= 7 ,-1,0
       0     .06       0      50     .07       0     100     .05       0
  248.65     .07       0  418.65      .1       0  599.01    .045       0
  622.54      .1       0
Bank Sta=599.01,622.54
XS Rating Curve= 0 ,0
Exp/Cntr=0.3,0.1

Type RM Length L Ch R = 1 ,17627   ,619.1,629.3,624.8
XS GIS Cut Line= 4
2282262.59837176678555.8805801172282369.37540962678367.957342632
2282368.76493266677940.6508940772282335.42502139677709.653240375
#Sta/Elev= 30
       0 2046.94    35.3 2037.44    62.9 2032.17   136.5 2009.88   159.5 2006.75
   168.7 2003.52   196.3 2003.79   205.5 2005.44   238.9 2002.45   250.9 1999.85
   262.9 1992.77   266.9 1992.17     300  1993.4   354.9 1991.23   370.9 1994.55
   450.9 1993.21   498.9 1994.45  507.81 1991.74   514.9 1990.34  527.791991.747
   534.9 1993.94   610.9  1990.7   626.9  1997.6   667.2 1999.98   707.6  2013.6
   769.7 2038.07   816.6 2062.61   853.1 2083.64   869.2 2094.69   876.8 2097.81
#Mann= 7 ,-1,0
       0      .1       0     120     .07       0     150     .06       0
  226.14     .07       0  326.14      .1       0  507.81    .045       0
  527.79      .1       0
#XS Ineff= 1 ,-1
   421.3  500.18 1999.62
Permanent Ineff=
       F
Bank Sta=507.81,527.79
XS Rating Curve= 0 ,0
Exp/Cntr=0.3,0.1

Type RM Length L Ch R = 1 ,16998   ,519.3,511.9,503.7
XS GIS Cut Line= 4
2282603.56930618678640.3653093572282711.25289551678322.344134331
2282760.64734052678177.7728285732282769.16379299677890.052717707
#Sta/Elev= 30
       0 2040.61      16 2036.76    91.3  2012.9   117.4 2006.85   172.3 1999.49
   227.2 1995.53   235.6 1991.46   239.9  1990.8   244.1  1991.5   286.3 1990.02
   294.8 1987.93   324.3 1986.74   362.4 1987.98   370.8 1986.63  392.091985.437
   400.4 1983.44   417.3 1983.83  424.731985.435     430 1986.45   446.9 1985.93
   472.9 1988.13   517.1 1986.79   624.7 1988.46   637.2 1992.87   653.2 1994.91
   673.2 2002.56   701.2 2015.09   733.2 2025.48   749.1 2029.68   776.4 2039.71
#Mann= 7 ,-1,0
       0      .1       0      80     .05       0     200     .06       0
     300      .1       0  392.09    .045       0  424.73     .08       0
  508.53      .1       0
#XS Ineff= 2 , 0
                          552.13         1992.57
Permanent Ineff=
       F       F
Bank Sta=392.09,424.73
XS Rating Curve= 0 ,0
Exp/Cntr=0.3,0.1

Type RM Length L Ch R = 1 ,16486   ,156.2,182,199.1
XS GIS Cut Line= 4
2282870.51924319678657.7029296012283235.36915257678322.041012974
2283213.90739319678235.3355050992283314.34842707678090.254011723
#Sta/Elev= 30
       0  2018.8    59.9 2001.11    94.6 1994.77   128.9 1991.58   154.4 1990.15
   165.3 1990.48   191.2 1986.88   236.5 1984.81   321.4  1984.6   344.7  1982.6
   371.8 1983.56   431.8  1982.3     480 1983.03   500.8 1981.84  505.79 1979.38
     509 1978.31   521.4 1977.84   529.6 1979.53   537.9 1980.75   558.5 1980.84
   579.1 1982.07   603.1  1979.7   622.8 1983.69   636.4 1984.79     651  1984.3
     663 1995.38   670.4 2000.09   720.5 2018.84   748.3 2030.36   761.5 2036.73
#Mann= 6 ,-1,0
       0     .05       0     450     .06       0     480     .07       0
  505.79    .045       0   529.6     .07       0  565.77      .1       0
#XS Ineff= 2 , 0
          470.88  1988.5
Permanent Ineff=
       F       F
Bank Sta=505.79,529.6
XS Rating Curve= 0 ,0
Exp/Cntr(USF)=0,0
Exp/Cntr=0.3,0.1

Type RM Length L Ch R = 1 ,16304   ,61.5,67,73
XS GIS Cut Line= 6
2282892.49983568678675.2398317392283245.65159877678324.499319438
2283294.64705402678320.4699260122283398.71490505678313.419307693
2283585.54034688678301.0716491812283636.24338331678077.169775004
#Sta/Elev= 30
       0 2021.66    59.7 2003.72    83.3 1998.46   122.1 1992.88   148.3 1991.91
   207.7 1986.02   343.4 1982.56   596.5 1983.25   611.5 1981.83   626.71976.284
   640.6 1974.64   659.4 1976.35   660.7  1976.6   668.7 1985.92   688.7 1987.03
   700.8 1989.52   769.4 1991.19     801 1995.76   838.4 1997.43   846.5 2002.96
   862.9 2009.64   887.4 2012.09   928.5 2027.62   964.3 2043.27   977.6  2050.6
     986 2052.98   994.2    2058  1013.4 2063.27  1022.9 2069.35    1068 2091.79
#Mann= 7 ,-1,0
       0     .05       0     450     .06       0     460     .07       0
  576.89     .06       0   626.7    .045       0   659.4     .06       0
  771.05      .1       0
Bank Sta=626.7,659.4
XS Rating Curve= 0 ,0
Exp/Cntr=0.3,0.1

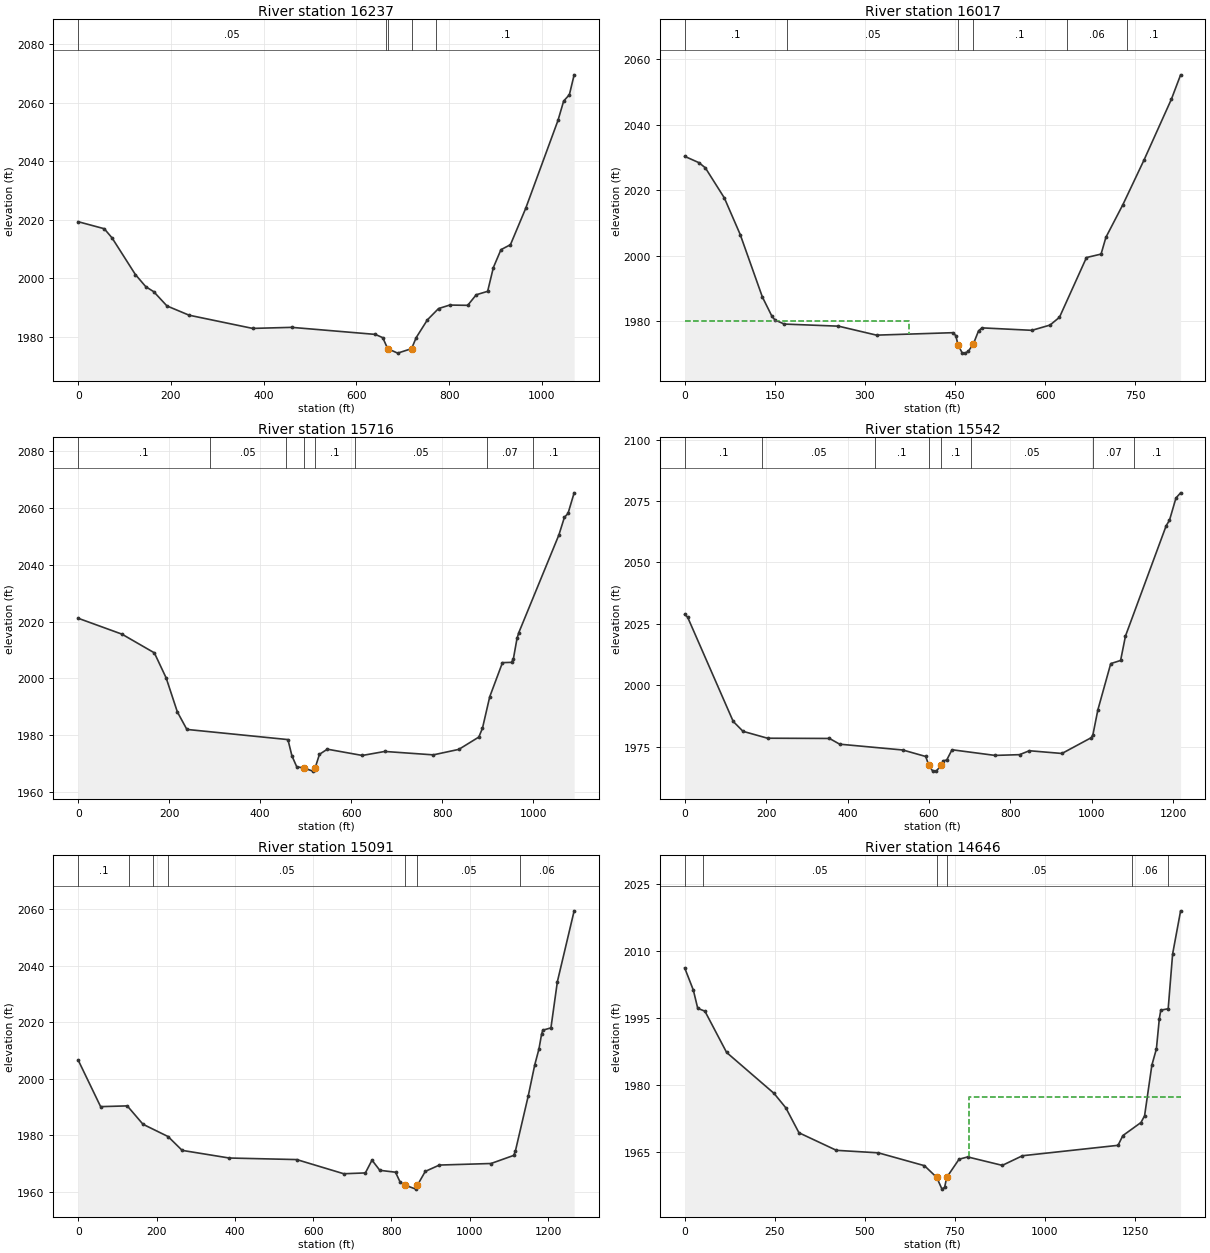
Type RM Length L Ch R = 1 ,16237   ,241.3,220,204.1
XS GIS Cut Line= 6
 2282893.9038334678721.2344576872283237.61242236678372.210886136
2283296.05105174 678366.464551962283400.11890278678359.413933641
2283586.94434461678347.0662751292283637.64738103678123.164400952
#Sta/Elev= 30
       0 2019.31    56.2 2016.91    73.1 2013.75   123.3 2001.24   145.9 1997.05
   162.9 1995.37   191.4 1990.49   239.2 1987.32   376.2  1982.8   460.4 1983.16
   640.9 1980.75   656.9 1979.62   667.5 1975.87     689 1974.34     7191975.871
   729.1 1979.68   753.2 1985.74   777.2 1989.59   801.3 1990.79   840.1  1990.7
   858.5 1994.31   883.1 1995.49   895.4 2003.61   911.8 2009.74   932.3 2011.45
   965.1 2023.85  1034.8 2053.97  1047.1 2060.62  1059.4 2062.78  1069.7 2069.58
#Mann= 5 ,-1,0
       0     .05       0  662.88     .06       0   667.5    .045       0
     719     .06       0  772.73      .1       0
Bank Sta=667.5,719
XS Rating Curve= 0 ,0
Exp/Cntr=0.3,0.1

Type RM Length L Ch R = 1 ,16017   ,296.9,301.1,303.8
XS GIS Cut Line= 3
2283308.42712638678851.222297117 2283690.3935821678407.292203099
2283726.73926006678170.318382839
#Sta/Elev= 30
       0  2030.3    23.8 2028.36    34.4 2026.79      66 2017.61    92.4 2006.44
   129.3 1987.37   145.2 1981.49   150.4 1980.33   165.8  1979.1     256 1978.46
   319.3 1975.72   446.6 1976.47   451.2 1975.57  454.931972.743   461.8 1970.31
   467.1 1970.23   472.3 1970.85   480.6 1973.09   489.1 1977.04   494.8 1977.94
   577.9 1977.19     608 1978.79   623.8 1981.18   668.7 1999.41     693 2000.46
   701.1  2005.6   729.4 2015.59   764.5 2029.18   810.1 2047.77   825.4 2055.18
#Mann= 6 ,-1,0
       0      .1       0     170     .05       0  454.93    .045       0
   480.6      .1       0  635.64     .06       0  735.64      .1       0
#XS Ineff= 2 , 0
           373.7 1979.92
Permanent Ineff=
       F       F
Bank Sta=454.93,480.6
XS Rating Curve= 0 ,0
Exp/Cntr(USF)=0,0
Exp/Cntr=0.3,0.1

Type RM Length L Ch R = 1 ,15716   ,195.9,173.5,160.7
XS GIS Cut Line= 4
2283358.20657932678959.9319418552283740.37831202678767.961259954
2283849.55019945678694.8133002172283837.36190355678163.648966825
#Sta/Elev= 30
       0 2021.21    96.2 2015.61   167.4 2009.03   193.3 2000.22     218 1988.21
   238.9 1982.05   461.1 1978.47   469.9 1972.73   480.4 1968.91   495.8 1968.47
     516 1967.36   521.11968.579   530.4 1973.28   547.7 1975.09   624.6 1972.88
     674 1974.29   780.8 1973.09   836.8 1975.02   880.8 1979.36   888.8 1982.47
   904.8 1993.56   932.8 2005.58   952.8 2005.68   956.8 2006.93   964.8 2014.12
   968.8 2016.19  1056.9 2050.59  1068.9 2056.74  1076.9 2058.15  1090.4  2065.4
#Mann= 8 ,-1,0
       0      .1       0     290     .05       0  457.68      .1       0
   495.8    .045       0   521.1      .1       0  609.09     .05       0
  899.09     .07       0  999.09      .1       0
Bank Sta=495.8,521.1
XS Rating Curve= 0 ,0
Exp/Cntr=0.3,0.1

Type RM Length L Ch R = 1 ,15542   ,444.6,450.9,457.7
XS GIS Cut Line= 4
  2284017.911945679332.2290498672284038.68698093678966.220778095
2283920.78631384678672.7237868082283913.81314966678137.716264333
#Sta/Elev= 30
       0 2028.85     7.1 2027.78   119.2 1985.29   143.3 1981.26   203.4 1978.46
   355.6 1978.36   380.7 1976.03   535.8 1973.66   591.9 1971.02  599.651967.372
   609.1  1965.1   617.7 1965.06  629.78 1967.37     635 1969.23   643.6 1969.62
   656.5 1973.76     762 1971.46   822.4 1971.76   846.4 1973.36   926.5 1972.25
   998.5 1978.68  1002.5 1979.85  1014.7 1990.01  1046.3 2008.83  1070.5 2010.11
  1082.5 2020.07  1182.5 2064.99  1190.5 2067.16  1206.5 2076.26  1217.9 2078.35
#Mann= 8 ,-1,0
       0      .1       0     190     .05       0   466.6      .1       0
  599.65    .045       0  629.78      .1       0  702.89     .05       0
 1002.89     .07       0 1102.89      .1       0
Bank Sta=599.65,629.78
XS Rating Curve= 0 ,0
Exp/Cntr=0.3,0.1

Type RM Length L Ch R = 1 ,15091   ,445.5,444.9,446.1
XS GIS Cut Line= 4
2284289.94730595679374.2762637162284333.98747935 678594.32241307
2284339.39117409678437.9928054872284255.72785974678119.865727189
#Sta/Elev= 30
       0 2006.63    57.2  1990.2   125.3 1990.46   165.4 1983.97   229.5 1979.62
   265.5 1974.73   385.7 1972.03     558 1971.48   678.1 1966.47   733.4 1966.76
   750.3 1971.28   770.3 1967.68   810.4 1967.01   822.4 1963.44  835.331962.421
   862.4 1961.03   866.31962.423   886.4  1967.3   922.4 1969.54  1054.3 1970.09
  1112.2 1972.95  1116.3 1974.37  1149.4 1994.01  1165.9 2004.93  1176.7 2010.58
  1183.3 2015.73  1186.6 2017.23  1207.3 2018.04  1223.8 2034.42  1266.6 2059.43
#Mann= 7 ,-1,0
       0      .1       0     130     .05       0     190     .06       0
     230     .05       0  835.33    .045       0   866.3     .05       0
 1127.62     .06       0
Bank Sta=835.33,866.3
XS Rating Curve= 0 ,0
Exp/Cntr=0.3,0.1

Type RM Length L Ch R = 1 ,14646   ,248.1,243.6,241.2
XS GIS Cut Line= 4
2284709.20010758679393.2472886862284746.44407286678886.306718557
2284751.85548887678413.7000088472284666.76640536678027.554521117
#Sta/Elev= 30
       0 2006.24    24.1 2001.25    36.2 1997.19    56.2 1996.54   116.4  1987.3
   247.9 1978.14   280.8 1974.89   317.2 1969.31   421.1 1965.38   537.4 1964.82
   665.4 1961.94  699.351959.328   714.1 1956.69   721.4 1957.09  727.331959.329
   761.5 1963.39   785.5  1963.9   881.5 1962.01   937.5 1964.17  1202.7  1966.5
  1216.1 1968.68  1266.4 1971.61  1276.4 1973.12  1296.6 1984.46  1309.2  1988.1
  1317.3 1994.87  1321.4 1996.77  1341.9 1997.09  1354.2 2009.36  1376.4 2019.02
#Mann= 6 ,-1,0
       0      .1       0      50     .05       0  699.35    .045       0
  727.33     .05       0 1240.94     .06       0 1340.94     .08       0
#XS Ineff= 2 , 0
                          789.46         1977.34
Permanent Ineff=
       F       F
Bank Sta=699.35,727.33
XS Rating Curve= 0 ,0
Exp/Cntr=0.3,0.1

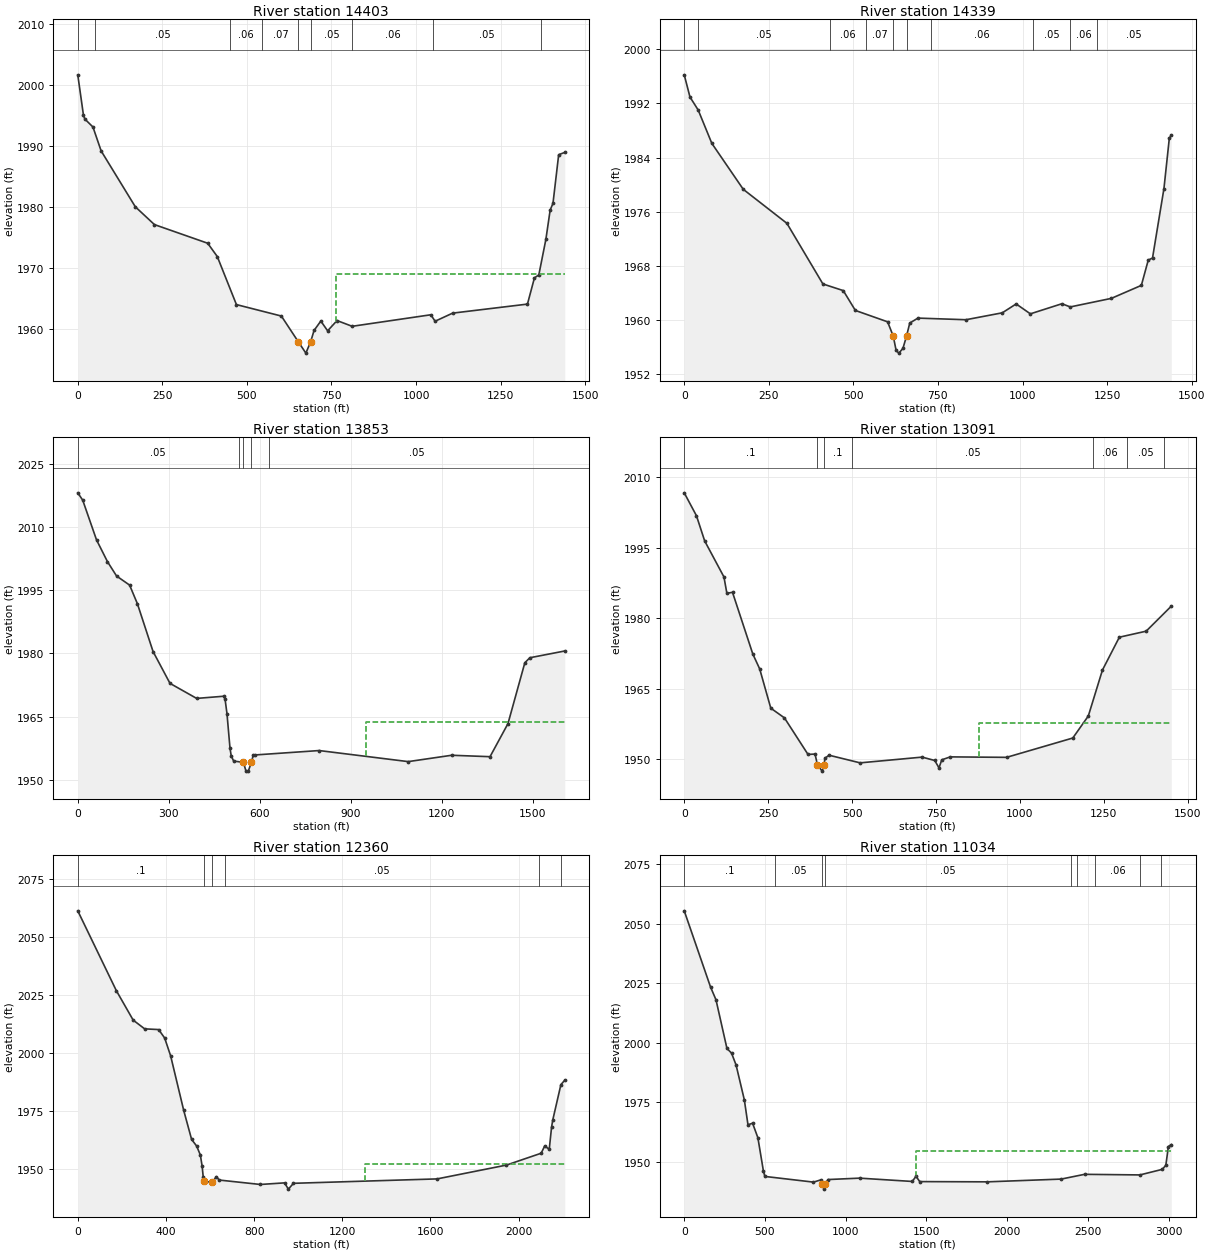
Type RM Length L Ch R = 1 ,14403   ,60.4,63.6,60.4
XS GIS Cut Line= 6
2284929.30249383679385.6361423862285001.99804559678864.768567409
 2284981.9468733678648.716363401 2284998.4096272678537.962141168
2285020.63541252678455.8233693292284868.69331592677979.961174593
#Sta/Elev= 30
       0 2001.74    16.6 1995.21    20.7  1994.5    44.9 1993.18    69.1 1989.26
   170.1  1980.1   226.6 1977.18   384.1 1974.12   412.4 1971.94     469 1964.06
   601.9 1962.18  651.58 1957.99   674.3  1956.1  688.57 1957.99   698.5 1959.82
   718.5 1961.36   738.6 1959.76   766.4 1961.44   811.1  1960.5  1043.7 1962.39
  1056.3 1961.33  1108.2 1962.66  1329.3 1964.14    1350 1968.45  1362.9 1968.92
  1383.8 1974.76  1396.4 1979.55  1404.8 1980.67  1421.6 1988.64  1439.7 1989.02
#Mann= 9 ,-1,0
       0      .1       0      50     .05       0     450     .06       0
  545.92     .07       0  651.58    .045       0  688.57     .05       0
  811.28     .06       0 1050.18     .05       0 1370.18     .06       0
#XS Ineff= 2 , 0
                          762.47         1969.01
Permanent Ineff=
       F       F
Bank Sta=651.58,688.57
XS Rating Curve= 0 ,0
Exp/Cntr=0.3,0.1

Type RM Length L Ch R = 1 ,14339   ,481.9,486.4,491.1
XS GIS Cut Line= 6
 2284982.4511109 679374.040080482285055.14666266678853.172505502
2285035.09549037678637.1203014942285051.55824428678526.366079261
 2285073.7840296678444.2273074222284921.84193299677968.365112686
#Sta/Elev= 30
       0 1996.23      17 1992.95    41.3 1991.03    81.6 1986.11   174.5 1979.33
   303.5 1974.31   409.9 1965.36   470.1 1964.38   505.9 1961.45   601.2 1959.77
  617.941957.647   626.4 1955.54   634.5 1955.15   646.5 1955.85  657.061957.647
   666.7 1959.59   690.9 1960.32   832.7 1960.08   940.2  1961.1   981.2 1962.41
  1023.2 1960.95  1116.4 1962.44  1141.2 1961.97  1262.5 1963.23  1351.3 1965.15
  1371.7 1968.88  1384.3 1969.19  1418.1 1979.45    1434 1986.89  1439.7 1987.29
#Mann= 10 ,-1,0
       0      .1       0      40     .05       0     430     .06       0
  535.92     .07       0  617.94    .045       0  657.06     .07       0
   730.7     .06       0 1030.18     .05       0 1140.18     .06       0
 1220.18     .05       0
Bank Sta=617.94,657.06
XS Rating Curve= 0 ,0
Exp/Cntr=0.3,0.1

Type RM Length L Ch R = 1 ,13853   ,768,762,756.9
XS GIS Cut Line= 4
2285669.19092519679344.3494414232285508.23168628678933.933507975
2285616.35530338677983.7260762982285502.68732612677808.366154554
#Sta/Elev= 30
       0 2018.17    16.3 2016.43    61.9 2006.98    97.9 2001.82     128  1998.4
     171 1996.24   196.8 1991.79   248.3 1980.46   304.2 1972.89   392.1 1969.32
   481.9 1969.84   485.9 1969.08   492.1  1965.7     502 1957.54     506 1955.68
   514.1 1954.43   546.3 1954.13   554.3 1952.16   562.4 1952.04  572.59 1954.12
   578.5 1955.77   586.1 1955.89   796.1 1956.93  1089.8  1954.3  1233.1 1955.81
  1359.6 1955.47  1418.8 1963.33  1474.4 1977.79  1490.8 1978.98  1606.2 1980.59
#Mann= 5 ,-1,0
       0     .05       0  530.85      .1       0   546.3    .045       0
  572.59      .1       0  630.85     .05       0
#XS Ineff= 2 , 0
                           950.8         1963.72
Permanent Ineff=
       F       F
Bank Sta=546.3,572.59
XS Rating Curve= 0 ,0
Exp/Cntr=0.3,0.1

Type RM Length L Ch R = 1 ,13091   ,717.2,730.7,733.2
XS GIS Cut Line= 4
2286160.23251925679032.6750540642286235.58412988678692.150861456
2285988.13352353677910.1588735782285901.66366861 677642.03980668
#Sta/Elev= 30
       0 2006.68    36.4 2001.81    60.9 1996.45   118.3 1988.79     127 1985.32
   143.8 1985.52   204.3  1972.4   224.8 1969.23   257.8 1960.89   298.5 1958.82
   368.7 1951.05   389.6 1951.13   396.61948.903   410.6  1947.5  416.511948.821
     419 1950.25   431.6 1950.88   523.9 1949.26   708.5 1950.48   746.3 1949.76
   758.8 1948.19   767.2 1949.91   792.4 1950.53   960.2 1950.43  1157.4 1954.54
  1203.6 1959.22  1245.7 1968.99  1296.1 1975.98  1375.9 1977.26  1450.7 1982.57
#Mann= 7 ,-1,0
       0      .1       0   396.6    .045       0  416.51      .1       0
  498.76     .05       0 1218.97     .06       0 1318.97     .05       0
 1428.97     .07       0
#XS Ineff= 2 , 0
                          878.35         1957.77
Permanent Ineff=
       F       F
Bank Sta=396.6,416.51
XS Rating Curve= 0 ,0
Exp/Cntr=0.3,0.1

Type RM Length L Ch R = 1 ,12360   ,1263.3,1325.8,1329.9
XS GIS Cut Line= 4
2286649.79575107      679048.9332286907.20040738678566.572878052
2287026.08660603677899.314817413 2286274.4158252677261.994787604
#Sta/Elev= 30
       0 2061.28     175 2026.84   251.4 2014.13   303.5 2010.36     367 2010.05
   394.2 2006.42   421.4 1998.72   480.8 1975.15   516.6 1962.65   539.3 1959.82
   556.3 1955.93   564.4 1951.07   569.5 1946.25  574.691944.515  609.541944.156
   629.4 1946.62   641.6 1945.13   828.5 1943.22   938.2 1943.91   955.7 1941.21
   978.8 1943.72  1630.4 1945.62  1945.4 1951.59  2102.8  1956.7  2118.5 1959.78
  2139.5 1958.44    2150 1967.94  2155.2 1970.95  2192.3 1986.29    2210 1988.22
#Mann= 6 ,-1,0
       0      .1       0  574.69    .045       0  609.54      .1       0
  666.74     .05       0 2094.51     .07       0 2194.51     .06       0
#XS Ineff= 2 , 0
                         1305.62         1951.88
Permanent Ineff=
       F       F
Bank Sta=574.69,609.54
XS Rating Curve= 0 ,0
Exp/Cntr=0.3,0.1

Type RM Length L Ch R = 1 ,11034   ,733.5,738.1,728.1
XS GIS Cut Line= 5
2286697.10825647679044.0242396732287187.81840919678554.798092499
 2287393.8720844 678475.351667842287610.00263137678000.354039227
2286418.81166452676960.620768425
#Sta/Elev= 30
       0  2055.4   162.7 2023.47   196.7 2018.07   264.6 1997.64     293 1995.69
     321 1990.73   372.3 1976.07   394.9  1965.6   423.3 1966.28   456.2 1960.18
   490.1 1946.36   499.2 1943.95   800.5 1941.56   847.6 1942.53   855.3 1940.64
   867.7 1938.62  873.47 1940.61   890.5 1942.64  1086.3 1943.23  1412.7 1941.84
  1435.6 1944.03  1458.7 1941.78  1878.4 1941.68  2334.6 1942.83  2479.6 1944.83
  2822.6 1944.58  2961.2 1946.92  2983.1 1948.64    2999  1956.5  3016.7 1957.31
#Mann= 9 ,-1,0
       0      .1       0     560     .05       0   855.3    .045       0
  873.47     .05       0 2395.62     .06       0 2435.62     .05       0
 2545.62     .06       0 2825.62     .05       0 2955.62     .06       0
#XS Ineff= 2 , 0
                         1438.39         1954.72
Permanent Ineff=
       F       F
Bank Sta=855.3,873.47
XS Rating Curve= 0 ,0
Exp/Cntr=0.3,0.1

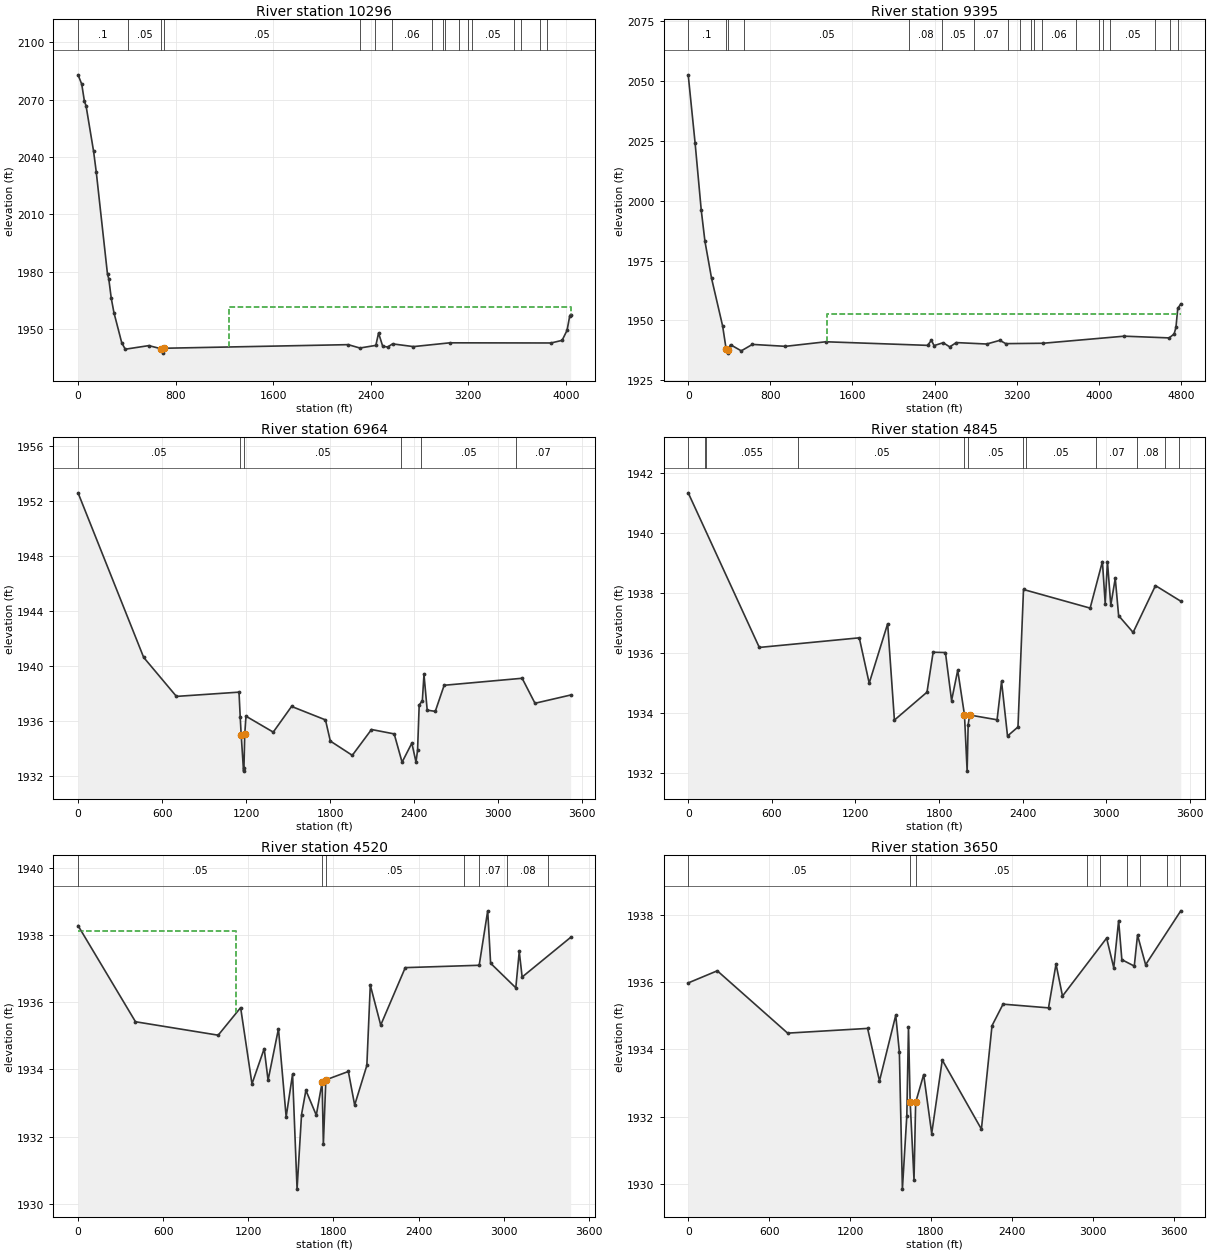
Type RM Length L Ch R = 1 ,10296   ,893.9,900.8,893.5
XS GIS Cut Line= 5
2286884.63474096679166.2826864152287180.91457059679030.131204205
2288115.57650055678741.671276584 2287836.5114222677618.376907496
 2286438.2102045676887.343109126
#Sta/Elev= 30
       0 2083.06    30.3 2078.16    52.3 2069.17    65.5 2066.89   127.2 2043.09
   149.2 2032.24   241.6 1978.49   251.7 1976.31   272.4 1965.97   294.4 1958.46
   358.2  1942.7     387 1939.29   580.6 1941.18     6811939.521   693.7 1937.24
  702.131939.791  2215.3 1941.68  2311.1 1939.92  2442.3  1941.3  2464.3 1947.79
  2498.2 1940.88  2538.8 1940.44  2579.4 1942.08  2750.9 1940.66  3048.8 1942.64
  3879.3 1942.56  3969.6 1943.93  4010.2 1949.17  4032.8 1956.95  4039.5 1957.32
#Mann= 17 ,-1,0
       0      .1       0  406.07     .05       0     681    .045       0
  702.13     .05       0 2314.23      .1       0 2434.23     .05       0
 2571.67     .06       0 2901.67     .05       0 2991.67     .06       0
 3011.67     .07       0 3121.67     .05       0 3201.67     .07       0
 3231.67     .05       0 3571.67     .06       0 3631.67     .05       0
 3791.67     .07       0 3841.67     .06       0
#XS Ineff= 2 , 0
                         1241.51         1961.42
Permanent Ineff=
       F       F
Bank Sta=681,702.13
XS Rating Curve= 0 ,0
Exp/Cntr=0.3,0.1

Type RM Length L Ch R = 1 ,9395    ,2426.9,2430.9,2380.1
XS GIS Cut Line= 6
2286913.17562689  679640.12475922287627.99330857679576.212684911
2287884.64149279679427.6138060712288384.96779038678692.497649781
2288003.05078939677613.4515410052286433.85300206676837.166711798
#Sta/Elev= 30
       0 2052.68    67.1 2024.19     127  1996.1   163.2    1983   227.3 1967.62
   335.6 1947.58   370.21937.802   383.9 1936.28   387.9 1937.79   412.1 1939.81
   516.8 1937.23   625.6 1939.93   947.6 1939.12  1341.3 1941.03  2331.7 1939.53
  2369.8 1941.63  2395.3 1939.43  2484.4 1940.63  2548.1 1938.89  2611.7 1940.69
  2908.7 1940.09    3036 1941.62  3094.2 1940.25  3457.8 1940.41  4247.7 1943.37
    4685 1942.65  4734.1 1944.27    4752 1947.03  4769.8 1955.01  4799.2 1956.85
#Mann= 19 ,-1,0
       0      .1       0   370.2    .045       0   387.9      .1       0
  544.75     .05       0 2153.82     .08       0 2473.82     .05       0
 2783.82     .07       0 3118.46      .1       0 3228.46     .05       0
 3338.46     .06       0 3368.46     .05       0 3448.46     .06       0
 3778.46     .07       0 3998.46     .05       0 4038.46     .07       0
 4108.46     .05       0 4548.46     .06       0 4698.46     .05       0
 4768.46     .06       0
#XS Ineff= 2 , 0
                         1350.68          1952.6
Permanent Ineff=
       F       F
Bank Sta=370.2,387.9
XS Rating Curve= 0 ,0
Exp/Cntr=0.3,0.1

Type RM Length L Ch R = 1 ,6964    ,2101.4,2119.9,2064.6
XS GIS Cut Line= 5
2286684.76308213680503.6424000212287577.96755602680666.133242703
 2288060.9827823680309.0212395012288919.01357031679418.481430248
2288961.94031982678647.425556932
#Sta/Elev= 30
       0 1952.58   468.6  1940.6   702.5 1937.76  1149.4 1938.07  1158.11936.237
 1164.81 1934.98  1181.8 1932.32  1184.7 1932.57  1190.4 1934.99  1199.1 1936.32
  1393.9 1935.16  1524.7 1937.03  1766.8 1936.05  1801.4 1934.51  1958.3 1933.47
  2095.4 1935.35  2257.5 1935.03  2313.8 1932.97  2383.7 1934.36  2413.1 1932.98
  2424.4 1933.83    2436 1937.13  2458.6 1937.45  2470.2 1939.36  2493.2 1936.76
  2550.9 1936.67  2614.3 1938.57  3171.2 1939.08  3262.9 1937.26  3517.4 1937.86
#Mann= 6 ,-1,0
       0     .05       0  1158.1    .045       0  1184.7     .05       0
 2308.56     .07       0 2448.56     .05       0  3125.2     .07       0
Bank Sta=1164.81,1190.4
XS Rating Curve= 0 ,0
Exp/Cntr=0.3,0.1

Type RM Length L Ch R = 1 ,4845    ,314.4,324.7,315.3
XS GIS Cut Line= 4
2287343.95665809681369.056235724  2288418.115428680808.106655885
2289074.54578738679395.7867917512289122.28617716678631.940555374
#Sta/Elev= 30
       0 1941.34   510.2 1936.19  1227.6 1936.51  1298.8    1935  1431.2 1936.98
  1479.7 1933.77  1713.5  1934.7  1757.5 1936.03  1845.8 1936.02  1889.9 1934.42
    1934 1935.43  1982.41933.944  2001.5 1932.07  2008.91933.617  2019.4 1933.94
  2216.3 1933.78  2248.4 1935.06  2291.3 1933.24  2366.3 1933.54    2406 1938.12
  2884.1  1937.5  2972.2 1939.05  2992.3 1937.65  3008.3 1939.05  3032.3  1937.6
  3064.4 1938.49  3088.5 1937.25  3192.7 1936.69    3353 1938.25  3534.6 1937.73
#Mann= 12 ,-1,0
       0    .055       0     120     .05       0     130    .055       0
     790     .05       0  1982.4    .045       0  2008.9     .05       0
 2401.81     .07       0 2421.81     .05       0 2929.23     .07       0
 3219.23     .08       0 3419.23     .07       0 3519.23     .08       0
Bank Sta=1982.4,2019.4
XS Rating Curve= 0 ,0
Exp/Cntr(USF)=0,0
Exp/Cntr=0.3,0.1

Type RM Length L Ch R = 1 ,4520    ,861.5,869.6,854.1
XS GIS Cut Line= 4
2287768.05496059681456.7722159522288523.04396777681040.040841449
2289137.55643346679871.2180213892289310.18697458678594.332628295
#Sta/Elev= 30
       0 1938.28   404.8 1935.42   987.6 1935.02  1145.8 1935.84  1225.8 1933.57
  1311.8 1934.62  1339.2 1933.68  1412.4 1935.21  1466.6 1932.59  1511.8 1933.86
  1543.5 1930.44  1575.1 1932.66  1605.8 1933.38    1679 1932.64 1720.12 1933.62
  1728.8 1931.77 1746.331933.691    1905 1933.94  1949.4 1932.94  2035.3 1934.12
  2059.6 1936.51    2133 1935.32    2306 1937.03    2827  1937.1    2887 1938.72
  2907.5 1937.16  3085.1 1936.43  3109.3 1937.51  3129.7 1936.75  3471.4 1937.93
#Mann= 7 ,-1,0
       0     .05       0 1720.12    .045       0 1746.33     .05       0
 2722.88     .08       0 2822.88     .07       0 3022.88     .08       0
 3312.88      .1       0
#XS Ineff= 2 , 0
         1114.44 1938.12
Permanent Ineff=
       F       F
Bank Sta=1720.12,1746.33
XS Rating Curve= 0 ,0
Exp/Cntr=0.3,0.1

Type RM Length L Ch R = 1 ,3650    ,791.5,786.6,786
XS GIS Cut Line= 4
2287958.37962813681575.3151806662289234.71619277680762.093793126
2289421.05933693679939.3326982692289383.06598825678644.500421386
#Sta/Elev= 30
       0 1935.97   215.6 1936.33   737.3 1934.48  1330.2 1934.62  1418.3 1933.06
  1538.9 1935.01  1565.7 1933.92  1588.2 1929.85    1621 1932.03  1633.3 1934.67
  1645.8 1932.43  1674.3 1930.13  1686.61932.425    1746 1933.25  1805.5  1931.5
  1883.8 1933.68  2174.1 1931.63  2252.6  1934.7  2334.5 1935.34  2671.6 1935.23
  2727.3 1936.53  2775.3 1935.58  3102.5  1937.3  3155.5 1936.42  3191.5 1937.82
  3215.5 1936.66  3307.6 1936.47  3331.6 1937.39  3391.6 1936.51  3652.4 1938.11
#Mann= 9 ,-1,0
       0     .05       0  1645.8    .045       0  1686.6     .05       0
 2956.99     .08       0 3056.99     .07       0 3256.99     .08       0
 3346.99      .1       0 3546.99     .08       0 3646.99      .1       0
Bank Sta=1645.8,1686.6
XS Rating Curve= 0 ,0
Exp/Cntr(USF)=0,0
Exp/Cntr=0.3,0.1