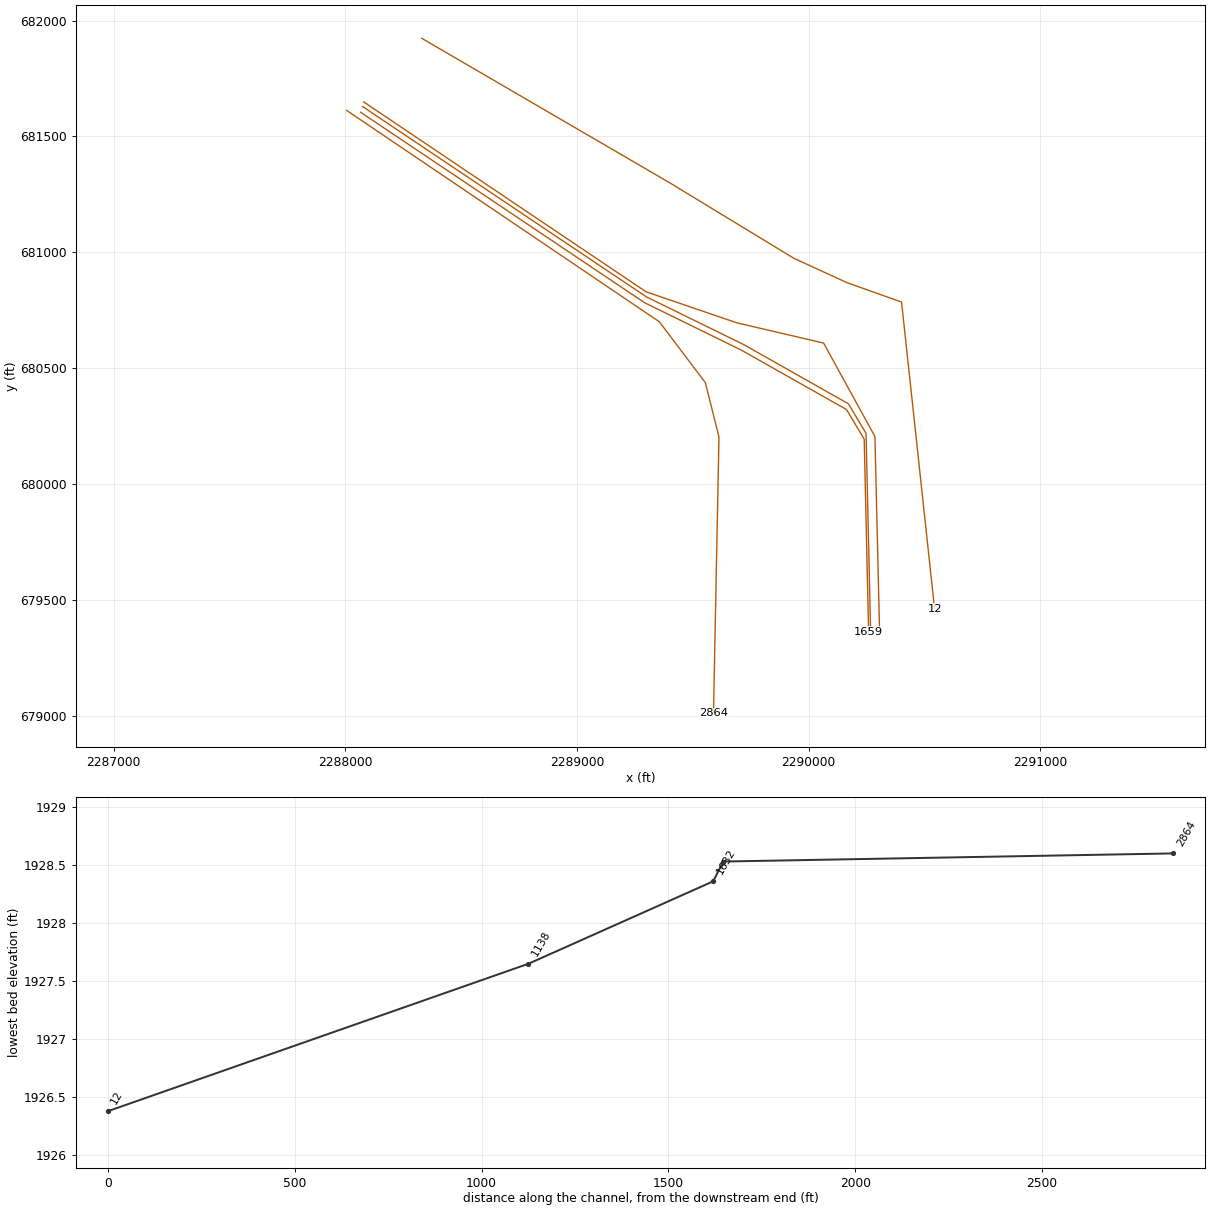
HEC-RAS study BEAVCK1.prj: BEAVCK1

--- BEAVCK1.g01 (geometry) --- (continued)

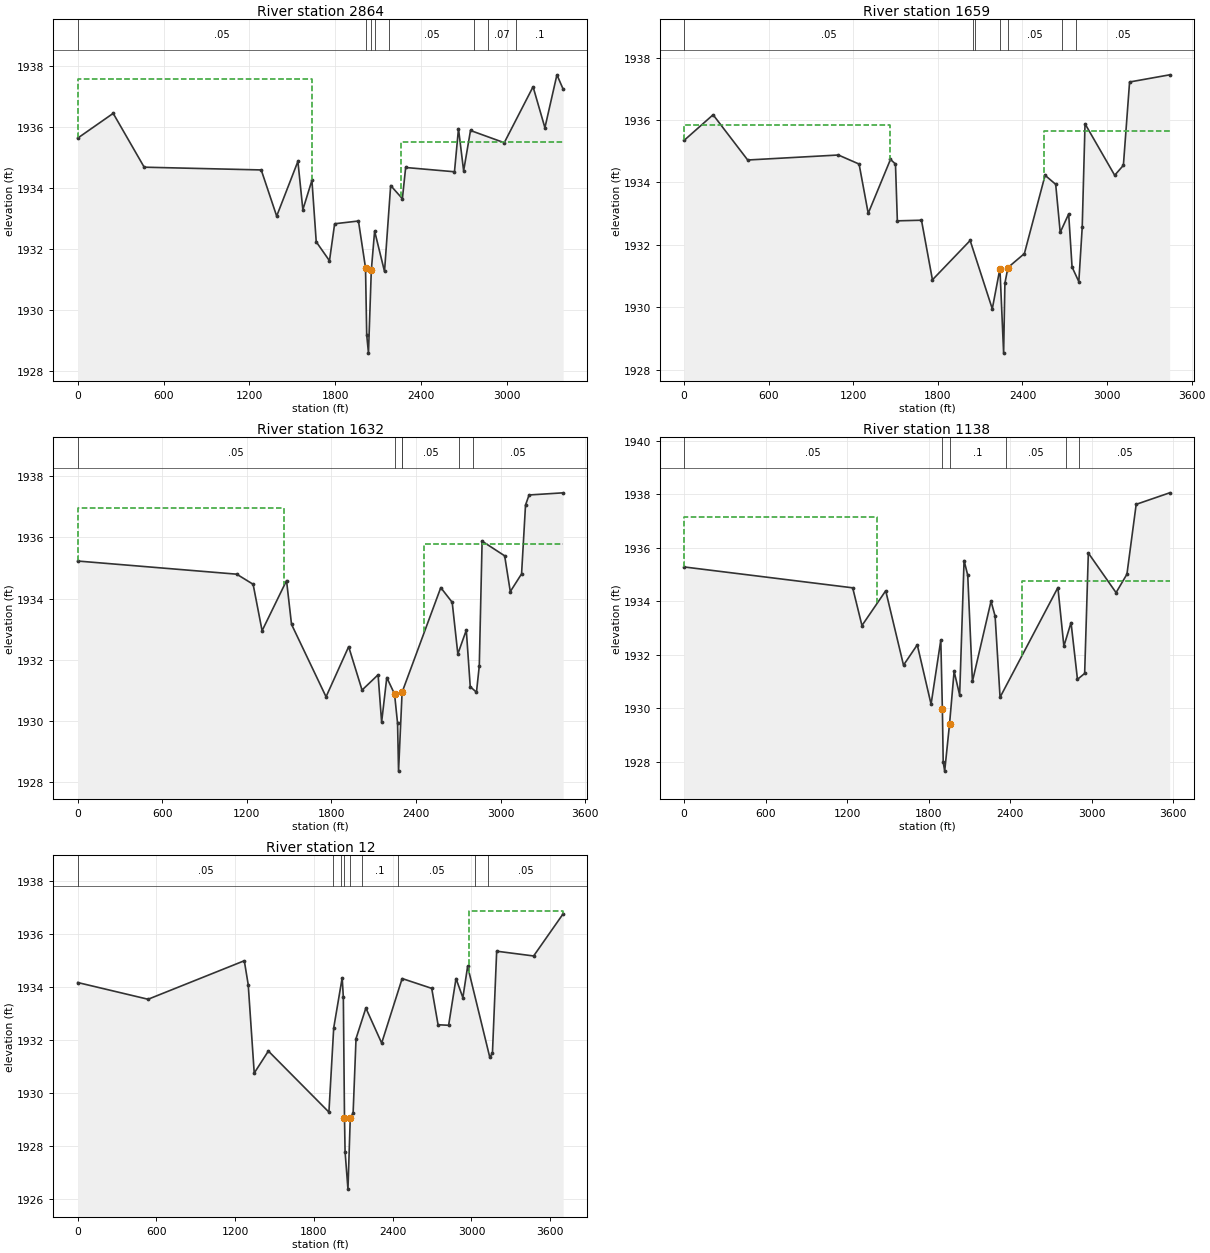
Type RM Length L Ch R = 1 ,2864    ,1134.8,1204.6,1170.7
XS GIS Cut Line= 5
2288005.81284803681612.1273170692289355.26640861680699.963021527
2289554.14995837680436.9656958522289612.87513683680202.355235312
2289589.21346219679009.464575364
#Sta/Elev= 30
       0 1935.63   248.1 1936.44   464.8 1934.68  1282.9 1934.59  1390.9 1933.08
  1539.3 1934.87  1573.9 1933.29  1637.3 1934.25  1667.4 1932.24    1760 1931.62
  1796.1 1932.83  1962.5 1932.92  2011.9 1931.39  2020.2  1929.2  2032.5  1928.6
 2052.361931.307  2075.5 1932.59  2144.7 1931.27  2187.6 1934.08  2269.6 1933.65
  2292.5 1934.67  2633.7 1934.53  2661.7 1935.94  2697.7 1934.56  2745.7 1935.88
  2981.7 1935.48    3183 1937.31  3265.8 1935.97  3349.8  1937.7  3393.5 1937.23
#Mann= 8 ,-1,0
       0     .05       0  2011.9    .045       0 2052.36     .05       0
 2078.55      .1       0 2178.55     .05       0  2770.4     .08       0
  2870.4     .07       0  3060.4      .1       0
#XS Ineff= 2 , 0
         1635.07 1937.57  2258.5         1935.49
Permanent Ineff=
       F       F
Bank Sta=2011.9,2052.36
XS Rating Curve= 0 ,0
Exp/Cntr(USF)=0,0
Exp/Cntr=0.3,0.1

Type RM Length L Ch R = 1 ,1659    ,25.9,26.6,25.8
XS GIS Cut Line= 6
2288065.69793125681604.350216552 2289291.7588009680782.130213057
2289709.39493566 680577.412471222290163.43037844680320.825214691
2290239.73885622680193.0085144132290258.81267035679361.195901134
#Sta/Elev= 30
       0 1935.35   205.3 1936.17   450.7 1934.72  1093.8 1934.88  1240.9 1934.59
  1305.6 1933.01  1463.6 1934.74    1499 1934.59  1512.3 1932.77  1683.5 1932.79
  1761.2 1930.88  2028.7 1932.14  2185.7 1929.95  2239.91931.238  2266.2 1928.53
  2275.2 1930.77  2296.81931.273  2413.4 1931.72  2560.3 1934.23  2635.5 1933.94
  2667.6  1932.4  2727.6 1932.99  2751.6 1931.29  2799.6 1930.82  2823.6 1932.56
  2843.6 1935.88    3054 1934.23  3115.7 1934.55  3159.6 1937.22  3443.8 1937.45
#Mann= 7 ,-1,0
       0     .05       0 2051.35      .1       0 2061.35     .05       0
  2239.9    .045       0  2296.8     .05       0 2681.73      .1       0
 2781.73     .05       0
#XS Ineff= 2 , 0
         1457.25 1935.83 2550.19         1935.65
Permanent Ineff=
       F       F
Bank Sta=2239.9,2296.8
XS Rating Curve= 0 ,0
Exp/Cntr(USF)=0,0
Exp/Cntr=0.3,0.1

Type RM Length L Ch R = 1 ,1632    ,437.8,494.4,450.6
XS GIS Cut Line= 6
2288073.73269667681629.3884072472289299.79356632680807.168403752
2289717.42970108680602.4506619152290171.46514386680345.863405386
2290247.77362164680218.0467051082290266.84743577679386.234091829
#Sta/Elev= 30
       0 1935.23  1127.9  1934.8  1244.4 1934.47  1308.1 1932.95  1481.5 1934.59
  1516.8 1933.16  1761.8 1930.79  1922.1 1932.43  2017.1 1931.01  2130.9 1931.51
  2155.9 1929.96  2192.6 1931.42  2247.7 1930.88  2269.1 1929.92    2276 1928.36
  2301.2 1930.94  2575.5 1934.36  2656.6 1933.88  2696.6 1932.19  2756.6 1932.97
  2784.6 1931.12  2828.7 1930.94  2848.7  1931.8  2868.7 1935.88  3028.7  1935.4
  3068.7 1934.23  3148.7 1934.81  3176.7 1937.06  3201.9 1937.39  3443.8 1937.46
#Mann= 6 ,-1,0
       0     .05       0  2247.7    .045       0  2301.2      .1       0
 2301.35     .05       0 2701.73      .1       0 2801.73     .05       0
#XS Ineff= 2 , 0
         1465.92 1936.95 2459.11         1935.79
Permanent Ineff=
       F       F
Bank Sta=2247.7,2301.2
XS Rating Curve= 0 ,0
Exp/Cntr(USF)=0,0
Exp/Cntr=0.3,0.1

Type RM Length L Ch R = 1 ,1138    ,1104.5,1125.6,1039.1
XS GIS Cut Line= 6
2288079.33034115681648.7479622762289298.44246702680829.060416422
 2289689.7693297680695.2839923632290064.47898545680607.889578934
2290286.05533003680204.3566546952290306.12184122  679358.9152111
#Sta/Elev= 30
       0 1935.28  1240.5  1934.5  1308.8 1933.09  1483.6 1934.39  1614.6 1931.61
    1716 1932.37  1817.5 1930.15  1889.2 1932.55 1900.781929.954  1906.8 1927.99
  1917.7 1927.65  1953.6 1929.42  1987.1 1931.38  2027.9 1930.49  2060.4 1935.52
  2087.4 1934.97  2121.9    1931  2258.9    1934  2288.9 1933.44  2325.3 1930.41
  2751.1 1934.51  2795.1 1932.32  2847.8  1933.2  2895.1 1931.08    2948  1931.3
  2975.1  1935.8  3179.2 1934.32  3259.2 1935.01  3327.3 1937.62  3573.6 1938.05
#Mann= 6 ,-1,0
       0     .05       0 1900.78    .045       0  1953.6      .1       0
 2367.52     .05       0 2807.89      .1       0 2907.89     .05       0
#XS Ineff= 2 , 0
         1422.48 1937.13 2483.75         1934.76
Permanent Ineff=
       F       F
Bank Sta=1900.78,1953.6
XS Rating Curve= 0 ,0
Exp/Cntr(USF)=0,0
Exp/Cntr=0.3,0.1

Type RM Length L Ch R = 1 ,12      ,,,
XS GIS Cut Line= 6
2288330.17340984681923.2271954692289399.90569315681299.861775515
2289936.65750714680973.4749014412290165.40020392680868.757252454
2290401.04088598680784.8126368252290543.37070418679461.386432542
#Sta/Elev= 30
       0 1934.16   536.4 1933.53  1269.4 1934.98  1299.3 1934.08  1345.1 1930.75
  1452.8 1931.58  1914.2 1929.28  1950.7 1932.45  2015.3 1934.34  2024.1  1933.6
  2032.9 1929.07  2037.3 1927.79  2059.3 1926.38  2076.9 1929.07  2098.5 1929.24
  2120.8 1932.05  2195.7  1933.2  2316.1 1931.88  2472.2 1934.31  2697.5 1933.94
  2745.8 1932.57  2826.3 1932.55  2882.6 1934.31  2934.9 1933.59  2971.1 1934.77
  3140.1 1931.34  3160.2 1931.51  3192.4 1935.34    3474 1935.16  3699.1 1936.75
#Mann= 9 ,-1,0
       0     .05       0  1946.3      .1       0  2006.3    .025       0
  2032.9    .045       0  2076.9    .025       0 2167.88      .1       0
 2438.02     .05       0 3028.02      .1       0 3128.02     .05       0
#XS Ineff= 2 , 0
                         2983.39         1936.86
Permanent Ineff=
       F       F
Bank Sta=2032.9,2076.9
XS Rating Curve= 0 ,0
Exp/Cntr(USF)=0,0
Exp/Cntr=0.3,0.1
LCMann Table=0

Chan Stop Cuts=-1
Use User Specified Reach Order=0
Composite Channel Slope=5